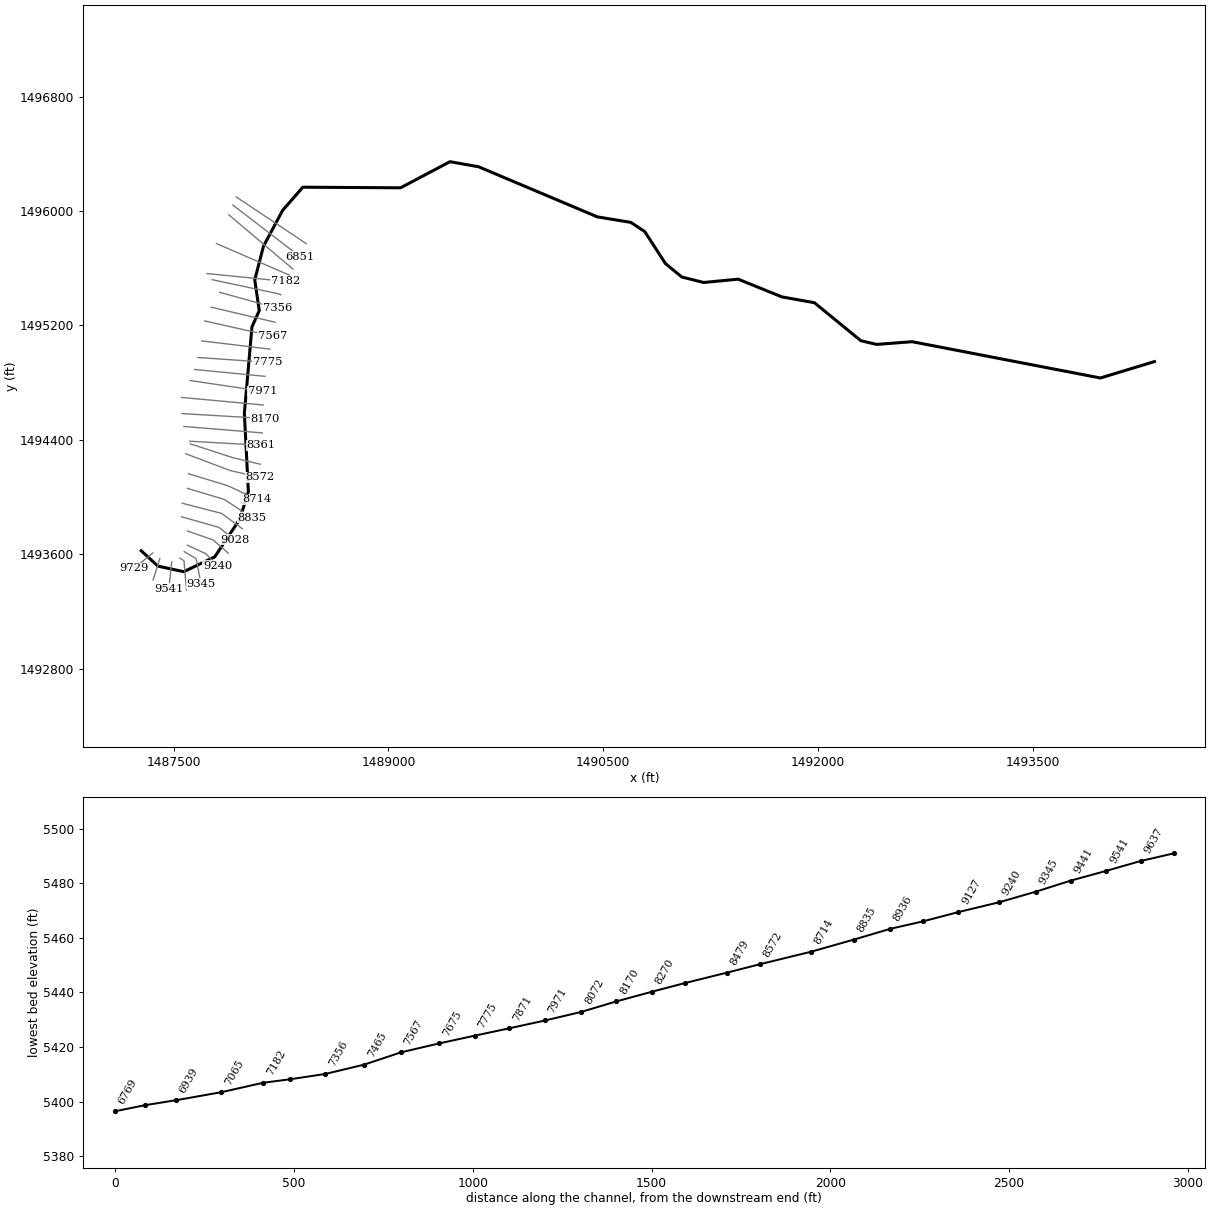
--- MirehavenArroyo.prj (project) ---

Proj Title=MirehavenArroyo
Current Plan=p02
Default Exp/Contr=0.3,0.1
English Units
Geom File=g01
Geom File=g02
Geom File=g03
Geom File=g04
Geom File=g05
Geom File=g06
Geom File=g07
Geom File=g08
Geom File=g09
Flow File=f01
Flow File=f02
Plan File=p01
Plan File=p02
Plan File=p04
Plan File=p05
Y Axis Title=Elevation
X Axis Title(PF)=Main Channel Distance
X Axis Title(XS)=Station
BEGIN DESCRIPTION:
Mirehaven Arroyo Model for FEMA LOMR in the area of the Mirehaven Planned Community. Model created by BHI October 2016, updated October 2017 to reflect supplemental as-built data. New Mexico State Plane Central Coordinates NAD83 and NAVD88
END DESCRIPTION:
DSS Export Rating Curves= 0
DSS Export Rating Curve Sorted= 0
DSS Export Volume Flow Curves= 0
DXF OffsetX= 0
DXF OffsetY= 0
DXF ScaleX= 1
DXF ScaleY= 10

--- MirehavenArroyo.p02 (plan) ---

Plan Title=MirehavenImprovementsSub
Program Version=4.10
Short Identifier=Existing_Sub
Geom File=g01
Flow File=f02
Subcritical Flow
K Sum by GR= 0
Std Step Tol= 0.01
Critical Tol= 0.01
Num of Std Step Trials= 20
Max Error Tol= 0.3
Flow Tol Ratio= 0.001
Split Flow NTrial= 30
Split Flow Tol= 0.02
Split Flow Ratio= 0.02
Log Output Level= 0
Friction Slope Method= 1
Unsteady Friction Slope Method= 2
Unsteady Bridges Friction Slope Method= 1
Calc Critical at every XS
Parabolic Critical Depth
Global Vel Dist= 0 , 0 , 0
Global Log Level= 0
CheckData=True
Encroach Param=-1 ,0,0, 0
Computation Interval=1HOUR
Output Interval=1HOUR
Run HTab= 0
Run UNet= 0
Run PostProcess= 0
Run WQNet= 0
UNET Theta= 1
UNET Theta Warmup= 1
UNET ZTol= 0.02
UNET ZSATol= 0.05
UNET MxIter= 20
UNET MaxInSteps= 0
UNET DtIC= 0
UNET DtMin= 0
UNET MaxCRTS= 20
UNET WFStab= 2
UNET SFStab= 1
UNET WFX= 1
UNET SFX= 1
UNET DSS MLevel= 4
UNET DZMax Abort= 100
UNET Convert EG Bridges= 0
UNET Use Existing IB Tables=-1
UNET Froude Reduction=False
UNET Froude Limit= 1
UNET Froude Power= 10
UNET Time Slicing=0,0, 5
UNET Junction Losses=0
Instantaneous Interval=1HOUR
Write IC File= 0
Write IC File at Sim End=0
Echo Input=False
Echo Parameters=False
Echo Output=False
Write Detailed= 0
WQ AD Non Conservative
WQ ULTIMATE=-1
WQ Max Comp Step=1HOUR
WQ Output Interval=15MIN
WQ Output Selected Increments= 0
WQ Output face flow=0
WQ Output face velocity=0
WQ Output face area=0
WQ Output face dispersion=0
WQ Output cell volume=0
WQ Output cell surface area=0
WQ Output cell continuity=0
WQ Output cumulative cell continuity=0
WQ Output face conc=0
WQ Output face dconc_dx=0
WQ Output face courant=0
WQ Output face peclet=0
WQ Output face adv mass=0
WQ Output face disp mass=0
WQ Output cell mass=0
WQ Output cell source sink temp=0
WQ Output cell source sink nsm=0
WQ Output MaxMinRange=-1
WQ Daily Max Min Mean=-1
WQ Daily Range=0
WQ Daily Time=0
WQ Create Restart=0
WQ Fixed Restart=0
WQ System Summary=0
WQ Use Fixed Temperature=0
Sorting and Armoring Iterations= 10
XS Update Threshold= 0.02
Hydraulics Update Threshold= 0.02
Energy Slope Method= 1
Volume Change Method= 0
XS Weighting Method= 0
Number of US Weighted Cross Sections= 1
Number of DS Weighted Cross Sections= 1
Upstream XS Weight=0.25
Main XS Weight=0.5
Downstream XS Weight=0.25
Number of DS XS's Weighted with US Boundary= 1
Upstream Boundary Weight= 1
Weight of XSs Associated with US Boundary= 0
Number of US XS's Weighted with DS Boundary= 1
Downstream Boundary Weight= 0.5
Weight of XSs Associated with DS Boundary= 0.5
Sediment Output Level= 4
Mass or Volume Output= 0
Output Increment Type= 1
Profile and TS Output Increment= 10
XS Output Flag= 0
XS Output Increment= 10
Disregard all LS=0
Disregard all Conn=0
Disregard all Breaches=0
Disregard all Pumps=0

--- MirehavenArroyo.f02 (steady flow) ---

Flow Title=MirehavenArroyoA_FIS
Program Version=4.10
Number of Profiles= 1
Profile Names=FIS
River Rch & RM=MirehavenArroyo,MirehavenArroyoA,9729
     445
River Rch & RM=MirehavenArroyo,MirehavenArroyoA,6367
    1097
Boundary for River Rch & Prof#=MirehavenArroyo,MirehavenArroyoA, 1
Up Type= 2
Dn Type= 2
DSS Import GetInterval= 0
DSS Import GetPeak= 0
DSS Import FillOption= 0

--- MirehavenArroyo.g01 (geometry) ---

Geom Title=MirehavenArroyoImprovements
Program Version=4.10

River Reach=MirehavenArroyo ,MirehavenArroyoA
Reach XY= 30
      1487273.21      1493624.84      1487389.68      1493517.54
      1487570.56      1493478.53      1487786.85      1493581.92
      1487961.93      1493846.06      1488021.87       1494037.7
      1487993.77      1494585.48       1488046.8      1495189.94
      1488097.93      1495303.62      1488066.33      1495518.01
      1488127.38      1495754.15      1488260.63      1496003.75
      1488402.32      1496166.35      1489084.86      1496162.13
      1489430.14      1496344.64      1489629.57      1496309.22
      1490459.47      1495958.84       1490693.6      1495920.17
       1490790.8      1495855.69      1490934.53      1495632.91
       1491048.7      1495538.73       1491201.5      1495500.13
      1491442.83      1495523.42      1491748.66      1495399.35
      1491975.23      1495358.92      1492300.02      1495093.14
      1492410.38      1495067.27      1492658.07      1495086.29
        1493973.      1494832.58      1494350.37      1494947.25

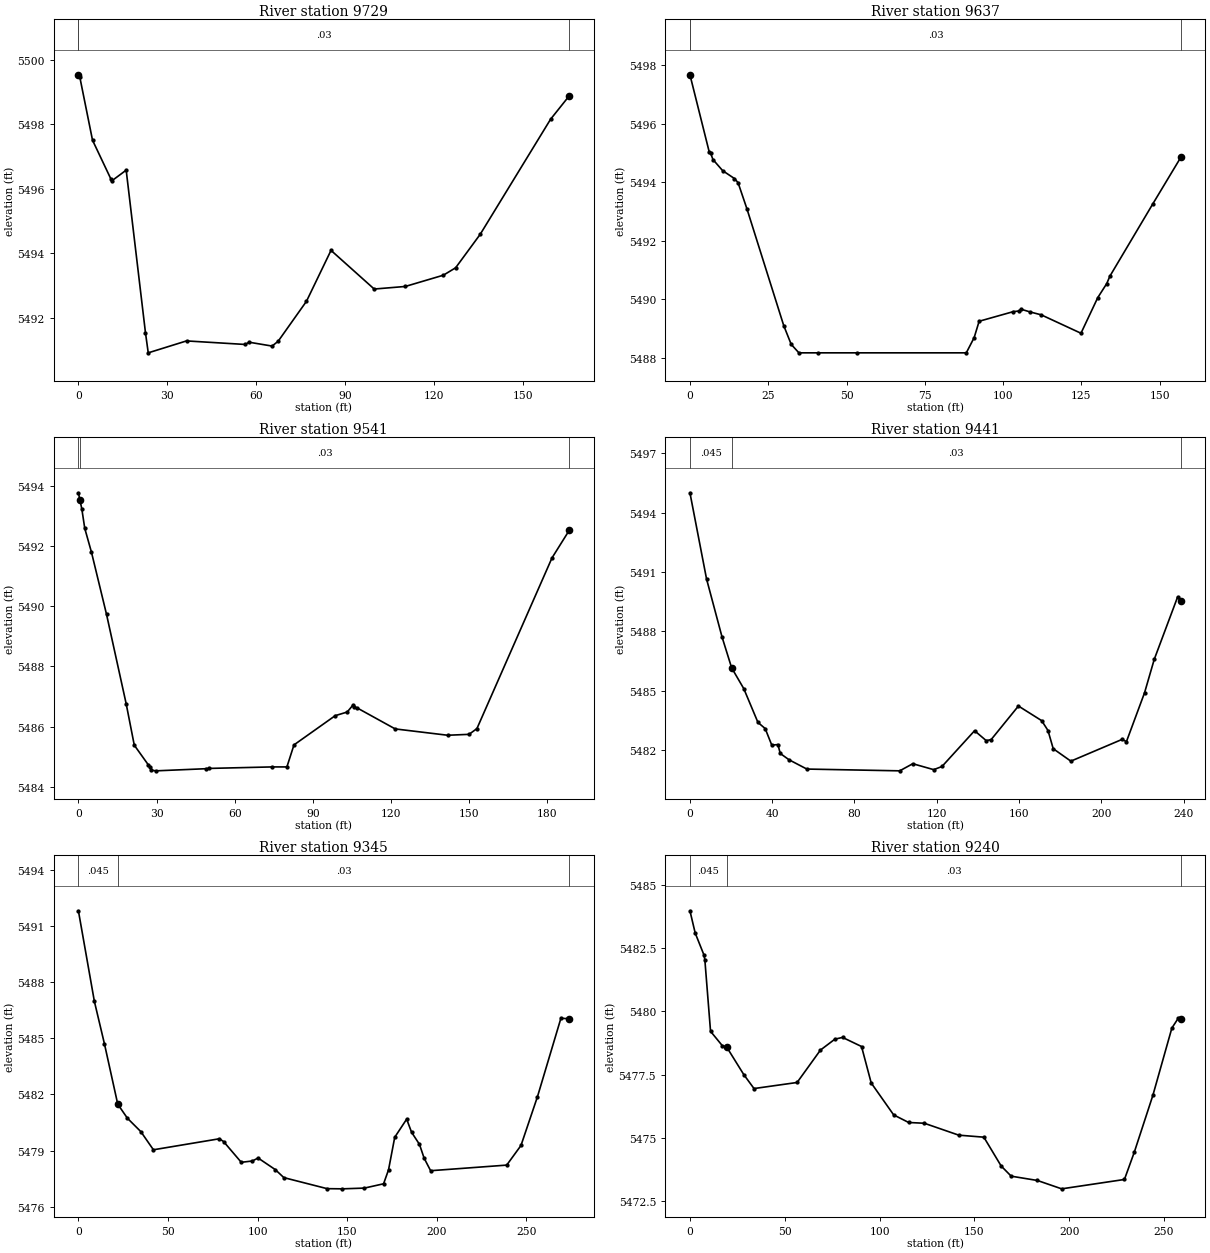
Type RM Length L Ch R = 1 ,9729    ,65.19,91.37,155.06
XS GIS Cut Line= 3
1487353.507985341493608.958326351487320.265414211493581.49015149
1487225.835851921493503.46346338
#Sta/Elev= 22
       0 5499.54.4499969 5499.484.759995 5497.5111.03999 5496.2911.29999 5496.25
   16.12 5496.5822.62999 5491.53   23.56 5490.91   36.47 5491.2856.28999 5491.17
57.56999 5491.24   65.34 5491.1267.38999 5491.2776.93999 5492.5185.21999 5494.09
99.78999 5492.89  110.27 5492.97  123.13 5493.32  127.26 5493.55  135.56 5494.59
  159.29 5498.16  165.62 5498.89
#Mann= 3 , 0 , 0
       0    .045       0       0     .03       0  165.62    .045       0
Bank Sta=0,165.62
XS Rating Curve= 0 ,0
Exp/Cntr=0.3,0.1

Type RM Length L Ch R = 1 ,9637    ,87.6,96.48,126.91
XS GIS Cut Line= 3
1487403.588200921493570.524350491487387.466554611493519.58007877
 1487356.28858921493421.05796067
#Sta/Elev= 27
       0 5497.676.139999 5495.046.630005 5494.987.360001 5494.7710.46001 5494.39
14.23001 5494.1215.37001 5493.98   18.22 5493.0829.96001 5489.09   32.34 5488.45
    34.8 5488.16   40.91 5488.1653.43001 5488.1688.25001 5488.16   90.76 5488.68
92.35001 5489.24  103.29 5489.57  105.03 5489.59  105.78 5489.65  108.59 5489.56
  112.17 5489.46  124.87 5488.83  130.24 5490.05  133.11 5490.53  134.09 5490.78
  147.73 5493.24  156.77 5494.85
#Mann= 3 , 0 , 0
       0    .045       0       0     .03       0  156.77    .045       0
Bank Sta=0,156.77
XS Rating Curve= 0 ,0
Exp/Cntr=0.3,0.1

Type RM Length L Ch R = 1 ,9541    ,84.1,100.03,124.3
XS GIS Cut Line= 3
1487486.400121391493547.600102811487481.050250141493497.83315532
1487466.262115361493360.26716658
#Sta/Elev= 28
       0 5493.76.5599976 5493.531.320007 5493.222.440002 5492.58 5.01001 5491.79
10.79001 5489.7318.32001 5486.77   21.45 5485.3926.74001 5484.75   27.64 5484.66
   27.92 5484.56    29.8 5484.54   48.78 5484.61   50.05 5484.62   74.36 5484.67
   80.02 5484.67   82.73  5485.498.57001 5486.37  103.16 5486.49  105.37 5486.72
  105.65 5486.67   107.1 5486.62  121.58 5485.93  141.72 5485.72  149.91 5485.75
  152.94 5485.94  181.75  5491.6  188.41 5492.52
#Mann= 3 , 0 , 0
       0    .045       0.5599976     .03       0  188.41    .045       0
Bank Sta=0.5599976,188.41
XS Rating Curve= 0 ,0
Exp/Cntr=0.3,0.1

Type RM Length L Ch R = 1 ,9441    ,76.47,96.13,113.52
XS GIS Cut Line= 4
1487544.148278251493573.037619431487572.044343881493555.27127424
1487578.320514671493481.897493421487589.570959941493350.37020817
#Sta/Elev= 30
       0 5495.018.080002 5490.65   15.62 5487.7120.29001 5486.1526.18001  5485.1
33.07001 5483.39   36.59 5483.08    39.8 5482.2442.79001 5482.27   43.91 5481.82
   48.19  5481.556.85001 5481.03  102.01 5480.94  108.36  5481.3  118.54    5481
  122.56 5481.16  138.41 5482.97  144.06 5482.47  146.46 5482.52  159.73 5484.22
  171.03 5483.48  174.11 5482.98  176.65 5482.06  185.23 5481.43  210.11 5482.53
  212.26 5482.42  221.06 5484.89  225.77 5486.58  237.18 5489.75  238.72 5489.54
#Mann= 3 , 0 , 0
       0    .045       020.29001     .03       0  238.72    .045       0
Bank Sta=20.29001,238.72
XS Rating Curve= 0 ,0
Exp/Cntr=0.3,0.1

Type RM Length L Ch R = 1 ,9345    ,66.41,104.84,169.37
XS GIS Cut Line= 4
1487573.397944971493618.964376671487656.953379741493569.54289141
1487666.491982941493520.18466302 1487690.52171871493395.84096603
#Sta/Elev= 30
       0 5491.838.919983 5486.9814.50998 5484.7221.95999 5481.48   27.34 5480.73
34.85999 5480.0141.85999 5479.04    78.7 5479.6381.01999 5479.4890.89999 5478.37
97.06999 5478.44  100.28  5478.6  109.86 5477.98  114.67 5477.55  138.78 5476.96
  147.35 5476.95  159.62 5476.99  170.32 5477.22  173.09 5477.97  176.54 5479.71
   183.2 5480.68  185.93 5479.98  190.35 5479.33  192.95 5478.59  196.57 5477.92
  239.04 5478.22     247 5479.27   256.2 5481.88  269.29 5486.08  273.99 5486.05
#Mann= 3 , 0 , 0
       0    .045       021.95999     .03       0  273.99    .045       0
Bank Sta=21.95999,273.99
XS Rating Curve= 0 ,0
Exp/Cntr=0.3,0.1

Type RM Length L Ch R = 1 ,9240    ,116.21,113,116.63
XS GIS Cut Line= 4
1487596.355985961493663.176840311487725.171971181493604.04970957
1487759.947592971493567.555762521487805.976288161493519.25270772
#Sta/Elev= 30
       0 5483.972.779999 5483.097.369995 5482.237.860001 5482.04   10.87 5479.21
      17 5478.65   19.45 5478.5828.40999  5477.533.78999 5476.9556.50999 5477.19
   68.83 5478.4776.42999  5478.9   80.47 5478.9790.48999 5478.61   95.59 5477.17
  107.43 5475.91  115.34 5475.61  123.59 5475.58  141.74 5475.11  154.98 5475.03
  164.13 5473.89   169.4 5473.49  183.23 5473.32  196.02 5472.99  229.11 5473.36
  234.28 5474.43   244.1 5476.68  254.13 5479.34  257.61 5479.74  258.87 5479.68
#Mann= 3 , 0 , 0
       0    .045       0   19.45     .03       0  258.87    .045       0
Bank Sta=19.45,258.87
XS Rating Curve= 0 ,0
Exp/Cntr=0.3,0.1

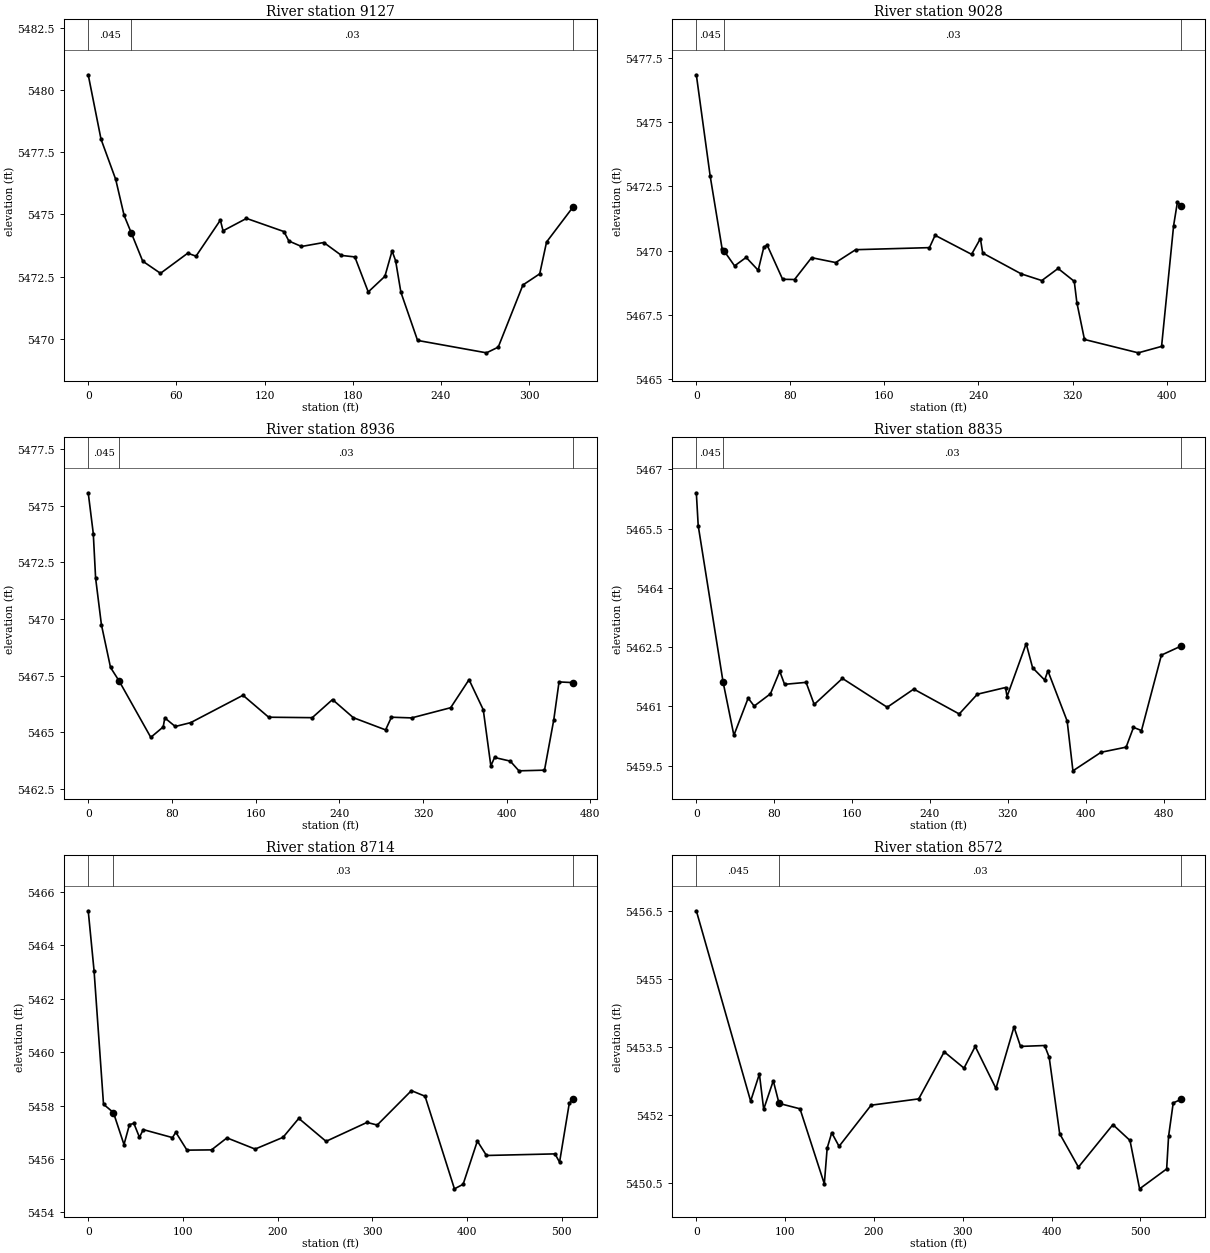
Type RM Length L Ch R = 1 ,9127    ,95.06,99.14,105.18
XS GIS Cut Line= 4
 1487595.87100031493763.152745791487774.750192871493700.75856169
1487832.434894631493650.693683031487880.804635421493608.71331165
#Sta/Elev= 30
       0 5480.628.700012 5478.0318.70001 5476.4124.42001 5474.9629.20999 5474.27
37.07001 5473.1249.17001 5472.6367.70999 5473.44   73.34 5473.32   89.91 5474.77
91.73001 5474.34  107.69 5474.84  133.19 5474.31  136.52 5473.93  145.11 5473.71
  160.27 5473.87  172.31 5473.35   181.4 5473.29  190.53 5471.88  201.86 5472.51
  206.73 5473.53  209.13 5473.14  212.73 5471.87  224.08 5469.93  270.98 5469.43
  278.97 5469.66  295.75 5472.16  307.19 5472.61  311.85 5473.89  329.88  5475.3
#Mann= 3 , 0 , 0
       0    .045       029.20999     .03       0  329.88    .045       0
Bank Sta=29.20999,329.88
XS Rating Curve= 0 ,0
Exp/Cntr=0.3,0.1

Type RM Length L Ch R = 1 ,9028    ,90.98,91.62,92.71
XS GIS Cut Line= 4
1487555.503461911493862.331699661487815.699491821493788.38099151
 1487887.20824291493733.328607021487928.132422151493701.82234216
#Sta/Elev= 30
       0 5476.84   11.75 5472.9121.98001 5470.0623.79001 5469.9832.53003 5469.41
   42.38 5469.7452.61002 5469.2457.48001 5470.1560.32001 5470.21   73.38 5468.89
83.51001 5468.8898.03003 5469.73  118.53 5469.54  135.52 5470.04  198.29 5470.12
  203.09  5470.6  234.11 5469.86  241.61 5470.47  243.58 5469.91  276.36  5469.1
  293.85 5468.84  307.68 5469.31  321.45 5468.81  323.68 5467.98  330.13 5466.55
  375.87 5466.03  395.72 5466.28  405.97 5470.98  409.23  5471.9  412.39 5471.73
#Mann= 3 , 0 , 0
       0    .045       023.79001     .03       0  412.39    .045       0
Bank Sta=23.79001,412.39
XS Rating Curve= 0 ,0
Exp/Cntr=0.3,0.1

Type RM Length L Ch R = 1 ,8936    ,99.07,101.05,107.46
XS GIS Cut Line= 4
1487560.813580241493956.856911041487835.205910581493885.84580213
1487937.823155261493809.689822251487979.800158631493778.53716527
#Sta/Elev= 30
       0 5475.584.839996 5473.787.059998 5471.8112.60999 5469.7521.31998 5467.86
   29.56 5467.26   59.81 5464.7771.66998 5465.2373.19998 5465.6383.19998 5465.25
97.91998 5465.42  147.95 5466.63  172.51 5465.66  214.15 5465.64  233.53 5466.44
  253.43 5465.64  284.28  5465.1  289.84 5465.66  309.17 5465.63  346.47 5466.08
  364.05 5467.32  377.65 5465.99  384.89 5463.51  388.46 5463.88  403.44 5463.72
  411.75 5463.29  436.18 5463.32  445.07 5465.55  450.08 5467.22  463.49 5467.19
#Mann= 3 , 0 , 0
       0    .045       0   29.56     .03       0  463.49    .045       0
Bank Sta=29.56,463.49
XS Rating Curve= 0 ,0
Exp/Cntr=0.3,0.1

Type RM Length L Ch R = 1 ,8835    ,115.84,121.19,136.73
XS GIS Cut Line= 4
1487596.004519121494060.874910221487854.712329341493983.31061275
1487979.072662611493900.862249481488044.75556519 1493857.3158254
#Sta/Elev= 30
       0 5466.411.920013 5465.5827.39999 5461.6338.58002 5460.2753.23001 5461.21
59.45999 5461.01   76.13 5461.32   85.69 5461.8990.64999 5461.56  112.76 5461.61
   121.1 5461.05  150.07 5461.71  196.11 5460.98  223.37 5461.44  270.08 5460.81
  288.69 5461.31  317.69 5461.48  319.18 5461.25  338.87 5462.59  345.46 5461.98
  357.84 5461.67   361.2  5461.9  380.97 5460.63   386.9 5459.37  415.79 5459.84
  441.55 5459.97  449.11 5460.47  457.34 5460.39  477.78  5462.3   498.1 5462.53
#Mann= 3 , 0 , 0
       0    .045       027.39999     .03       0   498.1    .045       0
Bank Sta=27.39999,498.1
XS Rating Curve= 0 ,0
Exp/Cntr=0.3,0.1

Type RM Length L Ch R = 1 ,8714    ,125.03,141.19,156.87
XS GIS Cut Line= 4
1487603.325253341494163.21009769 1487874.21874811494080.77542337
1488015.248304381494016.521238841488082.315663061493985.96481823
#Sta/Elev= 30
       0  5465.36.169983 5463.0516.13998 5458.0526.57999 5457.7437.76001 5456.54
   43.56 5457.2948.23001 5457.3354.10001 5456.8158.07001  5457.1   88.94  5456.8
92.45999    5457  104.24 5456.33  130.16 5456.34  146.46 5456.79   176.2 5456.37
  205.66 5456.81   222.3 5457.52  251.07 5456.66  294.35 5457.37  305.08 5457.27
  341.18 5458.56  355.59 5458.35  386.61 5454.88  395.77 5455.05   410.8 5456.67
  420.44 5456.13  492.72 5456.19  497.59 5455.88  507.82 5458.08  511.84 5458.25
#Mann= 3 , 0 , 0
       0    .045       026.57999     .03       0  511.84    .045       0
Bank Sta=26.57999,511.84
XS Rating Curve= 0 ,0
Exp/Cntr=0.3,0.1

Type RM Length L Ch R = 1 ,8572    ,99.37,93.95,91.27
XS GIS Cut Line= 4
 1487584.10640721494303.261991181487895.121069821494185.21493395
1488021.87266048 1494156.69918471488103.12139035 1494138.4203734
#Sta/Elev= 30
       0 5456.5161.13998  5452.3      71  5452.975.81998 5452.1286.63998 5452.75
   93.12 5452.25  116.72 5452.13   144.1 5450.47   147.3 5451.26  152.44  5451.6
   160.7  5451.3  196.78 5452.21  250.39 5452.35  279.08 5453.39  301.37 5453.03
  313.98 5453.51  337.34 5452.58  357.62 5453.94  364.99 5453.51  392.14 5453.53
  397.26 5453.27  409.07 5451.58  430.19 5450.84  469.01 5451.78  488.24 5451.43
  499.04 5450.36  529.52  5450.8  531.67 5451.52   536.9 5452.26  545.86 5452.34
#Mann= 3 , 0 , 0
       0    .045       0   93.12     .03       0  545.86    .045       0
Bank Sta=93.12,545.86
XS Rating Curve= 0 ,0
Exp/Cntr=0.3,0.1

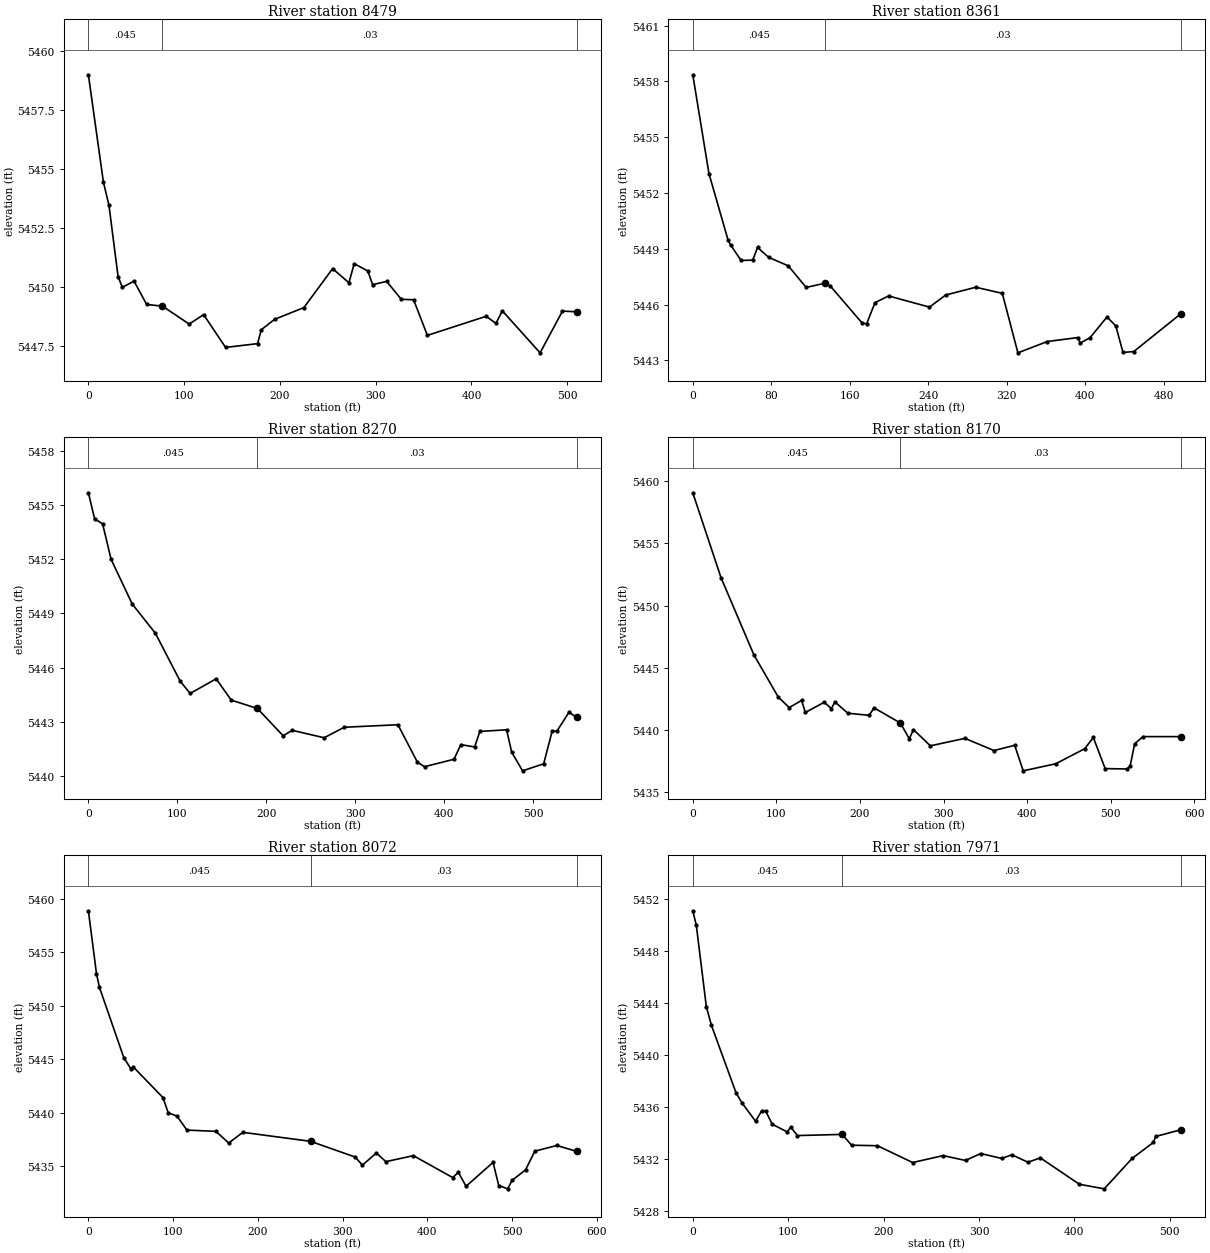
Type RM Length L Ch R = 1 ,8479    ,102.29,117.81,132.75
XS GIS Cut Line= 4
1487616.00630364 1494372.34122581487913.919993791494275.38906208
1488017.927922771494250.506183671488105.010722211494229.67247675
#Sta/Elev= 30
       0 5459.01   15.63 5454.47    21.5 5453.4731.04001 5450.44   35.47    5450
47.67999 5450.26   60.84 5449.27   77.38  5449.2  105.24 5448.44  120.31 5448.84
  143.23 5447.45  176.64 5447.61  180.57  5448.2  194.42 5448.64  225.04 5449.14
     255 5450.79  272.03 5450.19  277.56    5451  291.81 5450.69  296.78 5450.11
  311.45 5450.25  326.74 5449.49  339.57 5449.47  353.96 5447.96  415.32 5448.77
  425.52 5448.47  432.24    5449  471.65 5447.22  495.03 5448.99  509.78 5448.96
#Mann= 3 , 0 , 0
       0    .045       0   77.38     .03       0  509.78    .045       0
Bank Sta=77.38,509.78
XS Rating Curve= 0 ,0
Exp/Cntr=0.3,0.1

Type RM Length L Ch R = 1 ,8361    ,92.16,90.41,87.25
XS GIS Cut Line= 3
1487613.085501111494390.585878511488009.454447591494368.01583519
 1488110.06053161494362.28712285
#Sta/Elev= 30
       0 5458.36    16.5 5453.04   36.06 5449.4538.51001 5449.2149.23999 5448.37
   61.12 5448.3966.04001 5449.0777.26001 5448.54   97.38 5448.08  115.56 5446.92
  134.32 5447.14  139.97 5447.01  172.24 5445.03  177.17 5444.95  185.77  5446.1
  199.67 5446.46  241.33 5445.86   257.8 5446.51   288.5 5446.93  315.58  5446.6
  331.48  5443.4  361.54 5444.01  392.36 5444.22   395.1 5443.93  404.99 5444.21
  422.33 5445.33   431.3 5444.85  438.64 5443.42  449.64 5443.47  497.78 5445.51
#Mann= 3 , 0 , 0
       0    .045       0  134.32     .03       0  497.78    .045       0
Bank Sta=134.32,497.78
XS Rating Curve= 0 ,0
Exp/Cntr=0.3,0.1

Type RM Length L Ch R = 1 ,8270    ,97.4,99.93,104.98
XS GIS Cut Line= 3
1487572.069738111494493.627238331488002.951618271494458.19668686
1488119.217222241494448.63639979
#Sta/Elev= 30
       0 5455.67 6.98999 5454.2315.98999 5453.9525.53998 5451.99   49.25 5449.52
75.35999  5447.9  103.09 5445.26  114.41 5444.57  143.65 5445.38  160.69  5444.2
  190.04 5443.74  218.99 5442.23  229.27 5442.53  265.12 5442.12   287.7  5442.7
  348.09 5442.84  370.05 5440.76  378.06 5440.52  411.08 5440.93  418.81 5441.74
  434.39 5441.61  440.18 5442.47  470.27 5442.56     476 5441.32  488.24 5440.29
  511.94 5440.68  521.48 5442.48  526.95 5442.49  540.37 5443.53  548.99 5443.25
#Mann= 3 , 0 , 0
       0    .045       0  190.04     .03       0  548.99    .045       0
Bank Sta=190.04,548.99
XS Rating Curve= 0 ,0
Exp/Cntr=0.3,0.1

Type RM Length L Ch R = 1 ,8170    ,101.23,98.15,95.51
XS GIS Cut Line= 3
1487557.87364861  1494583.7571361487995.764658561494557.86501814
1488140.952202691494549.28020383
#Sta/Elev= 30
       0 5459.0733.82996 5452.2473.22998 5446.03  102.26 5442.66  115.41 5441.81
  130.15 5442.39  134.71 5441.42  157.23 5442.24  165.81 5441.73  170.05 5442.27
  185.47 5441.36  210.92 5441.19  216.89 5441.79  248.42 5440.57  258.98 5439.31
  264.04 5440.04  284.24 5438.74  325.61 5439.34  360.29 5438.36  385.11 5438.78
  395.33 5436.73  434.29  5437.3  468.94 5438.51  479.21 5439.41  493.35 5436.91
  519.34 5436.88  523.14 5437.09  528.69 5438.91  538.67 5439.48   584.1 5439.48
#Mann= 3 , 0 , 0
       0    .045       0  248.42     .03       0   584.1    .045       0
Bank Sta=248.42,584.1
XS Rating Curve= 0 ,0
Exp/Cntr=0.3,0.1

Type RM Length L Ch R = 1 ,8072    ,106.44,101.51,96.5
XS GIS Cut Line= 3
1487553.654091191494696.777293891487996.687823881494655.88387091
1488127.375136241494643.82101621
#Sta/Elev= 30
       0 5458.869.559998 5452.9813.06995  5451.741.73999 5445.1550.44995 5444.05
52.95996 5444.2787.96997 5441.4194.19998 5439.99  104.68 5439.67  116.21 5438.37
  150.51 5438.25   165.6 5437.16  182.27 5438.16  262.17 5437.32   314.9 5435.85
  323.36 5435.09   339.8 5436.23  351.08 5435.42   383.5 5435.98  430.06 5433.93
  436.58 5434.42   445.7 5433.12  477.53 5435.35  484.27 5433.19  494.88 5432.88
  499.94 5433.67   515.9 5434.65  526.85  5436.4  552.84 5436.93  576.16 5436.38
#Mann= 3 , 0 , 0
       0    .045       0  262.17     .03       0  576.16    .045       0
Bank Sta=262.17,576.16
XS Rating Curve= 0 ,0
Exp/Cntr=0.3,0.1

Type RM Length L Ch R = 1 ,7971    ,98.24,100.01,106.11
XS GIS Cut Line= 3
1487616.080294681494814.80408681 1488003.38835941494757.04832829
1488122.185736381494739.33314691
#Sta/Elev= 30
       0 5451.083.690002 5449.97   14.19 5443.72   19.56 5442.2845.46002 5437.08
   51.69 5436.3265.79001 5434.92   72.38 5435.74   76.44  5435.783.27002 5434.69
99.05002  5434.1  102.58 5434.47  109.74 5433.82  156.52 5433.91  166.46 5433.08
  193.55 5433.04  230.42 5431.75  262.32 5432.28  285.85 5431.91  301.72 5432.44
  324.05 5432.06  334.38 5432.35  351.28 5431.77  364.24 5432.11  405.23 5430.08
  431.26 5429.73  460.39 5432.06  482.67 5433.29  485.15 5433.75   511.7 5434.27
#Mann= 3 , 0 , 0
       0    .045       0  156.52     .03       0   511.7    .045       0
Bank Sta=156.52,511.7
XS Rating Curve= 0 ,0
Exp/Cntr=0.3,0.1

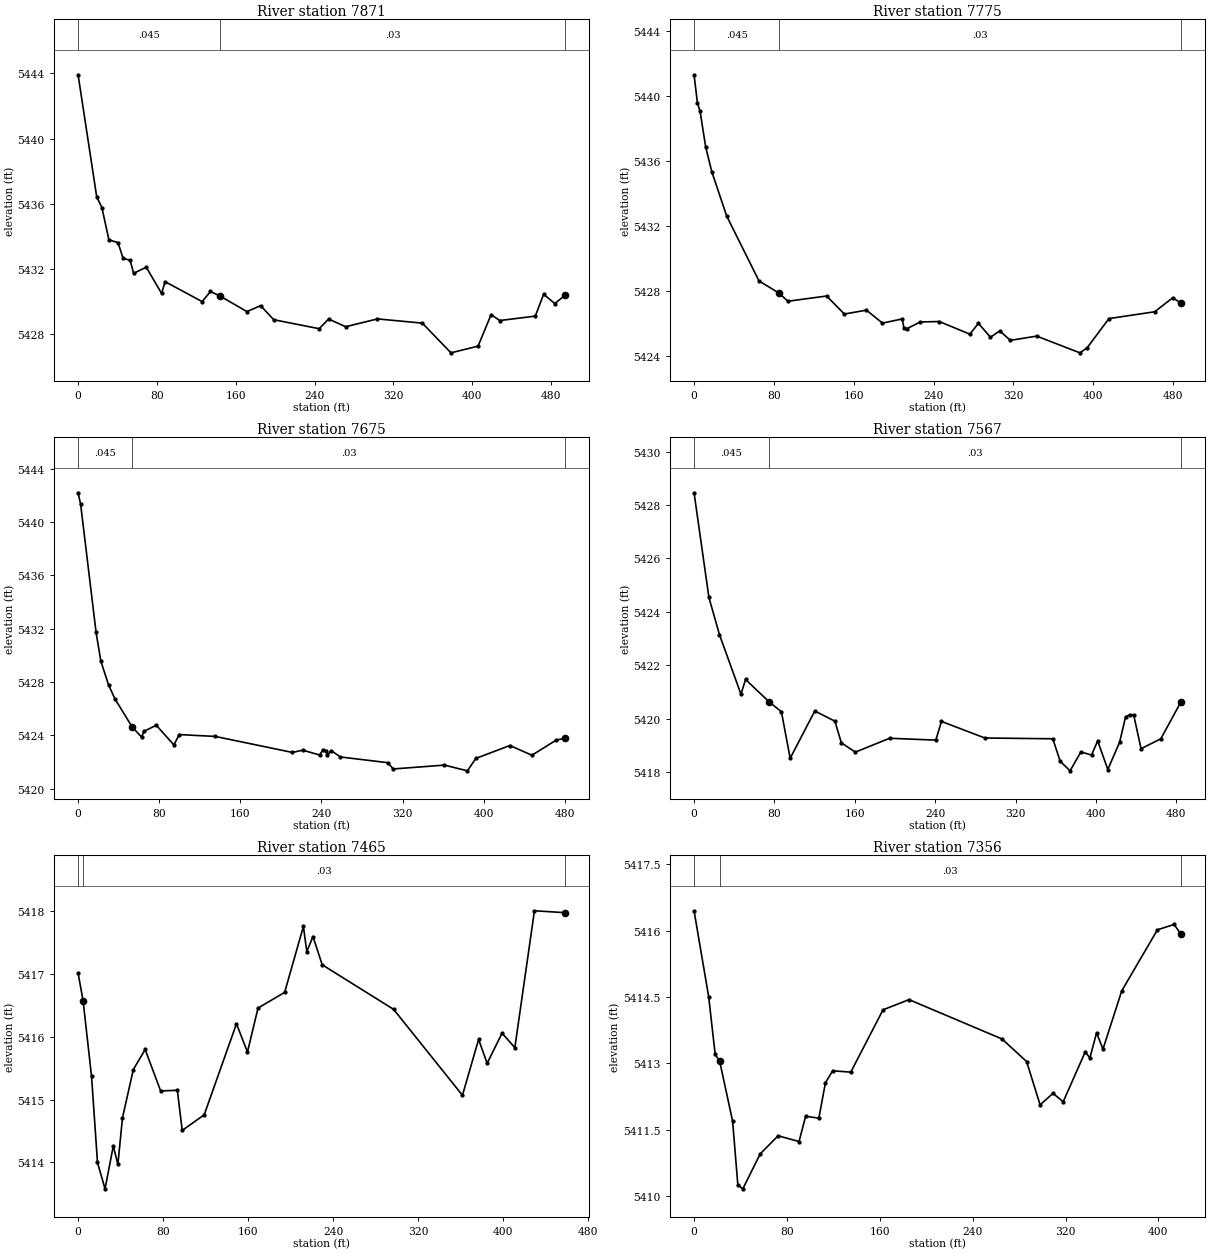
Type RM Length L Ch R = 1 ,7871    ,95.02,96.07,99.85
XS GIS Cut Line= 3
1487646.185201941494892.021846281488019.430152751494855.76921647
1488137.979730271494844.25470318
#Sta/Elev= 30
       0 5443.9118.87997 5436.4424.14999 5435.7731.25998  5433.840.53998 5433.62
45.69998 5432.6652.79999 5432.5456.38998 5431.7469.14999 5432.12   84.75 5430.51
88.26999 5431.23  125.89 5430.01  134.35 5430.63     144 5430.35  171.27  5429.4
  185.24 5429.76  198.47  5428.9  244.59 5428.35  254.15 5428.94  271.51 5428.47
  303.76 5428.95  349.27 5428.69  378.31 5426.87  405.82 5427.28  419.02 5429.21
  427.88 5428.85  463.88 5429.12  472.34 5430.46  483.63 5429.89  494.11  5430.4
#Mann= 3 , 0 , 0
       0    .045       0     144     .03       0  494.11    .045       0
Bank Sta=144,494.11
XS Rating Curve= 0 ,0
Exp/Cntr=0.3,0.1

Type RM Length L Ch R = 1 ,7775    ,111.48,99.94,93.57
XS GIS Cut Line= 3
1487669.11253198 1494975.73173941488031.444443851494950.97217346
1488156.051034071494942.45731461
#Sta/Elev= 30
       0 5441.323.390015 5439.586.059998 5439.0711.61002 5436.8817.77002 5435.35
   32.69 5432.6265.08002 5428.62   85.12 5427.8794.05002 5427.37  132.85 5427.69
  150.67 5426.58  172.77 5426.82  188.85 5426.02  208.61 5426.28  210.27 5425.74
  213.31 5425.68  226.74 5426.09   245.7 5426.12  276.42 5425.34  284.99 5426.01
  297.06 5425.15  306.32 5425.54  316.99 5424.96  343.43 5425.22  386.67 5424.19
  393.92  5424.5   415.8  5426.3  461.59 5426.72  479.69 5427.58  488.07 5427.25
#Mann= 3 , 0 , 0
       0    .045       0   85.12     .03       0  488.07    .045       0
Bank Sta=85.12,488.07
XS Rating Curve= 0 ,0
Exp/Cntr=0.3,0.1

Type RM Length L Ch R = 1 ,7675    ,129.16,107.3,92.34
XS GIS Cut Line= 3
1487696.101935521495091.741644451488037.852551551495050.70582812
1488172.98505786 1495034.4797485
#Sta/Elev= 30
       0 5442.192.519989 5441.33   17.75 5431.7222.48001 5429.5630.07001 5427.78
36.38998 5426.7353.35001 5424.6362.63998 5423.87   64.91  5424.3   77.12 5424.76
94.51999 5423.2899.66998 5424.06  135.25 5423.92  211.36 5422.72  221.54 5422.89
  238.14 5422.53   241.6 5422.91  244.86 5422.84  245.75 5422.52  249.81 5422.85
  258.72 5422.38   305.6 5421.95  310.72 5421.48  361.35 5421.77  383.96 5421.34
  392.27 5422.27  425.85 5423.24  447.61 5422.51  471.65 5423.65  480.31 5423.78
#Mann= 3 , 0 , 0
       0    .045       053.35001     .03       0  480.31    .045       0
Bank Sta=53.35001,480.31
XS Rating Curve= 0 ,0
Exp/Cntr=0.3,0.1

Type RM Length L Ch R = 1 ,7567    ,102.54,102.17,98.96
XS GIS Cut Line= 3
1487716.683873321495231.304728371488044.732554681495157.78390596
1488189.696958011495125.29512378
#Sta/Elev= 30
       0 5428.4614.79001 5424.54   25.28 5423.1546.67999 5420.92   51.28 5421.47
74.51999 5420.6486.95999 5420.2695.67001 5418.52  120.17 5420.29  140.15 5419.91
  146.62  5419.1  160.53 5418.75  194.64 5419.27  240.61  5419.2  246.27  5419.9
  289.44 5419.28  357.07 5419.25  364.41 5418.41  374.27 5418.05  385.04 5418.76
  395.62 5418.64  401.76 5419.17  411.83  5418.1  423.58 5419.12  429.52 5420.07
  433.55 5420.15  437.59 5420.14  444.95 5418.88   464.6 5419.25  484.75 5420.64
#Mann= 3 , 0 , 0
       0    .045       074.51999     .03       0  484.75    .045       0
Bank Sta=74.51999,484.75
XS Rating Curve= 0 ,0
Exp/Cntr=0.3,0.1

Type RM Length L Ch R = 1 ,7465    ,108.04,108.76,98.57
XS GIS Cut Line= 3
1487761.347684661495327.725790091488075.491460651495253.73470476
1488207.606256421495222.61736972
#Sta/Elev= 30
       0 5417.02 4.76001 5416.5712.67999 5415.3718.26999    541425.36002 5413.58
33.14001 5414.2637.48999 5413.97   41.78 5414.71      52 5415.48   63.13  5415.8
   77.72 5415.1493.45001 5415.15   98.03 5414.51  118.75 5414.76  149.11 5416.21
  159.47 5415.76  169.39 5416.46  194.46 5416.71  212.11 5417.76  215.33 5417.36
  221.13  5417.6  229.81 5417.15  297.02 5416.44  361.85 5415.07  377.06 5415.96
  385.09 5415.58  399.14 5416.06  411.17 5415.83  429.62 5418.01  458.47 5417.98
#Mann= 3 , 0 , 0
       0    .045       0 4.76001     .03       0  458.47    .045       0
Bank Sta=4.76001,458.47
XS Rating Curve= 0 ,0
Exp/Cntr=0.3,0.1

Type RM Length L Ch R = 1 ,7356    ,87.09,98.46,96.93
XS GIS Cut Line= 3
1487821.172526351495431.641624051488090.046853971495357.10146263
1488225.446533761495319.56454314
#Sta/Elev= 30
       0 5416.4512.62997  5414.5   18.19  5413.2   22.03 5413.05   33.22 5411.69
37.70999 5410.2542.00998 5410.1656.94998 5410.9572.38998 5411.3690.42999 5411.23
   96.09  5411.8  107.51 5411.76  113.17 5412.56   119.4 5412.83     135  5412.8
   162.8 5414.21  185.19 5414.44  265.28 5413.55  286.45 5413.04   298.1 5412.06
  309.18 5412.32  317.98 5412.13     337 5413.26  340.97 5413.12  346.75 5413.69
  352.24 5413.32  368.45 5414.64  399.17 5416.02  413.53 5416.14  419.52 5415.92
#Mann= 3 , 0 , 0
       0    .045       0   22.03     .03       0  419.52    .045       0
Bank Sta=22.03,419.52
XS Rating Curve= 0 ,0
Exp/Cntr=0.3,0.1

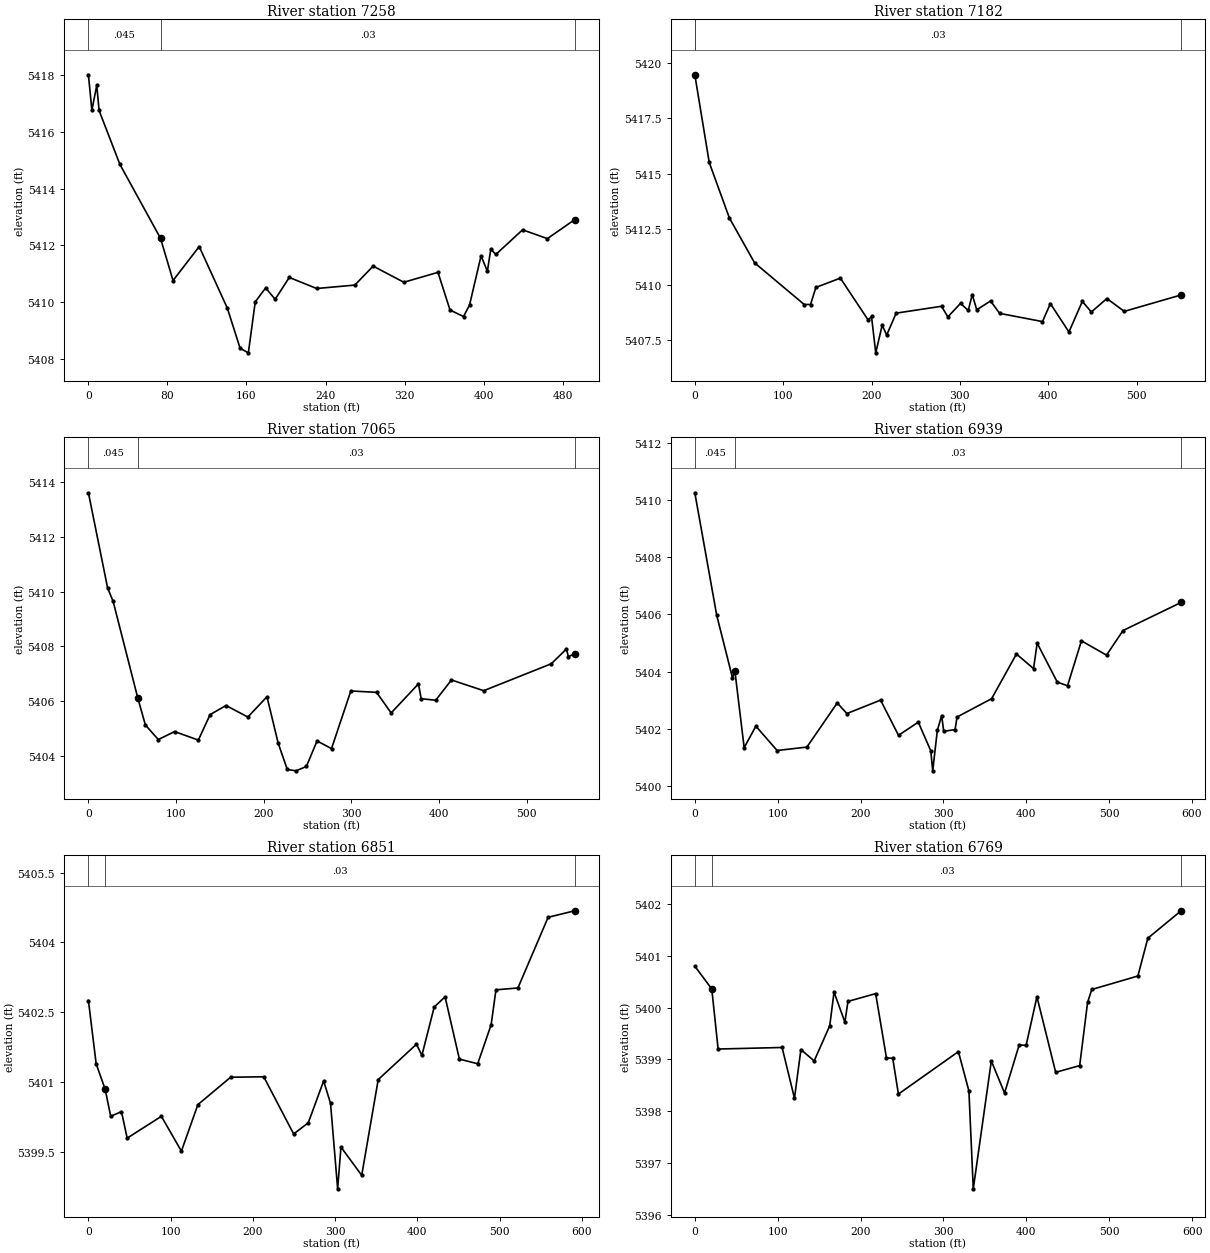
Type RM Length L Ch R = 1 ,7258    ,68.97,75.53,100.11
XS GIS Cut Line= 4
1487768.589558611495519.801739661488075.688124811495454.51010268
1488232.417444811495421.188182651488248.736796511495413.61649849
#Sta/Elev= 30
       0 5418.02     3.5 5416.778.440002 5417.6510.79001 5416.7631.85001 5414.86
      73 5412.25   85.63 5410.76  112.14 5411.96  140.57 5409.79  153.56 5408.37
  161.88 5408.21  168.87 5410.01  179.38  5410.5     189  5410.1  203.32 5410.87
  231.01 5410.48  269.66  5410.6  288.18 5411.27  319.25  5410.7  353.79 5411.05
  366.01 5409.72  379.68 5409.49  385.77  5409.9   397.4 5411.63  403.81 5411.09
  407.27 5411.87  412.34 5411.68  439.44 5412.55  464.53 5412.24  492.19 5412.91
#Mann= 3 , 0 , 0
       0    .045       0      73     .03       0  492.19    .045       0
Bank Sta=73,492.19
XS Rating Curve= 0 ,0
Exp/Cntr=0.3,0.1

Type RM Length L Ch R = 1 ,7182    ,168.16,117.26,52
XS GIS Cut Line= 3
1487732.746060041495562.874844971488069.166885361495528.99721414
1488280.438321591495507.72214678
#Sta/Elev= 30
       0 5419.4716.29004 5415.5239.02002 5413.0267.64001 5410.99  123.83 5409.11
     131 5409.11  137.04 5409.88  164.75  5410.3  196.23 5408.41  200.01 5408.57
  204.79 5406.93   212.1 5408.18  217.17 5407.73  227.93 5408.72  279.29 5409.03
  286.43 5408.55  300.76 5409.16  309.51 5408.84  314.07 5409.56  319.11 5408.87
   334.8 5409.27     345 5408.71  393.52 5408.34   402.5 5409.15  423.49 5407.87
  438.65 5409.25  448.88 5408.77  466.42 5409.38  486.11  5408.8  550.46 5409.54
#Mann= 3 , 0 , 0
       0    .045       0       0     .03       0  550.46    .045       0
Bank Sta=0,550.46
XS Rating Curve= 0 ,0
Exp/Cntr=0.3,0.1

Type RM Length L Ch R = 1 ,7065    ,193.48,126.19,49.02
XS GIS Cut Line= 3
 1487798.56650271495772.319171241488098.521593341495642.52222529
1488307.679403791495552.01519319
#Sta/Elev= 30
       0  5413.621.83997 5410.1428.22998 5409.6456.25998 5406.1364.98999 5405.14
79.68997 5404.6198.33997  5404.9  125.41 5404.59  138.84 5405.52     157 5405.85
   181.9 5405.43   203.7 5406.17  216.45 5404.48  226.86 5403.52  236.87 5403.47
  248.66 5403.63  260.84 5404.56  277.31 5404.28  299.35 5406.38  328.66 5406.33
  345.37 5405.58  376.53 5406.64  379.59  5406.1  396.11 5406.04  414.15 5406.78
  450.94 5406.39  527.99 5407.37  545.37 5407.91  547.41 5407.63  554.73 5407.73
#Mann= 3 , 0 , 0
       0    .045       056.25998     .03       0  554.73    .045       0
Bank Sta=56.25998,554.73
XS Rating Curve= 0 ,0
Exp/Cntr=0.3,0.1

Type RM Length L Ch R = 1 ,6939    ,88.92,87.87,100.31
XS GIS Cut Line= 3
1487885.375395131495972.930741921488132.515521661495763.75787567
1488333.358979731495593.76928507
#Sta/Elev= 30
       0 5410.25   26.44 5405.97   45.44 5403.7948.34003 5404.0359.55005 5401.35
73.68005  5402.199.35004 5401.25  135.26 5401.37  171.87 5402.91  183.55 5402.54
  224.17 5403.01  245.84 5401.78  269.73 5402.24  284.77 5401.24  287.12 5400.54
  292.67 5401.95  297.93 5402.47   300.4 5401.92   314.1 5401.98  316.49 5402.42
   358.2 5403.06  388.18 5404.62  408.81 5404.11  413.17    5405  437.42 5403.64
  449.81 5403.51  466.61 5405.08  496.88 5404.58   516.8 5405.44   586.9 5406.42
#Mann= 3 , 0 , 0
       0    .045       048.34003     .03       0   586.9    .045       0
Bank Sta=48.34003,586.9
XS Rating Curve= 0 ,0
Exp/Cntr=0.3,0.1

Type RM Length L Ch R = 1 ,6851    ,74.41,82.61,100.8
XS GIS Cut Line= 3
1487913.893078391496040.850859921488173.895884711495841.27422793
1488382.94501949 1495680.8093359
#Sta/Elev= 30
       0 5402.759.399963 5401.39   20.38 5400.8427.08997 5400.2640.21997 5400.36
   47.13 5399.79   88.72 5400.26  113.05 5399.51  133.08 5400.51  172.88  5401.1
  213.19 5401.11  249.53 5399.88  267.35 5400.12  286.01 5401.02  294.39 5400.54
  303.06  5398.7  307.07  5399.6  332.32 5398.99  352.39 5401.05  398.91 5401.81
  405.49 5401.57  420.46 5402.61  433.68 5402.83  451.08 5401.49  473.36 5401.39
   489.7 5402.23  495.55 5402.98  522.25 5403.02  558.99 5404.54   591.3 5404.68
#Mann= 3 , 0 , 0
       0    .045       0   20.38     .03       0   591.3    .045       0
Bank Sta=20.38,591.3
XS Rating Curve= 0 ,0
Exp/Cntr=0.3,0.1

Type RM Length L Ch R = 1 ,6769    ,179.94,138.74,104.17
XS GIS Cut Line= 3
1487937.739390061496097.64524563 1488212.79614581495914.14469402
1488425.760663281495772.06817485
#Sta/Elev= 30
       0  5400.820.45996 5400.3628.09998  5399.2  105.29 5399.23   120.2 5398.25
  127.99 5399.19  143.99 5398.97  162.78 5399.65  167.96  5400.3  181.04 5399.72
  184.77 5400.12  218.15 5400.27   231.2 5399.03  238.79 5399.02   245.6 5398.33
     318 5399.15  330.67 5398.39  335.93  5396.5  357.71 5398.97  373.66 5398.35
  391.32 5399.28  399.67 5399.27  412.73 5400.21  435.35 5398.75   464.3 5398.88
  473.83  5400.1  478.89 5400.35534.5099 5400.61  546.52 5401.34  586.66 5401.87
#Mann= 3 , 0 , 0
       0    .045       020.45996     .03       0  586.66    .045       0
Bank Sta=20.45996,586.66
XS Rating Curve= 0 ,0
Exp/Cntr=0.3,0.1