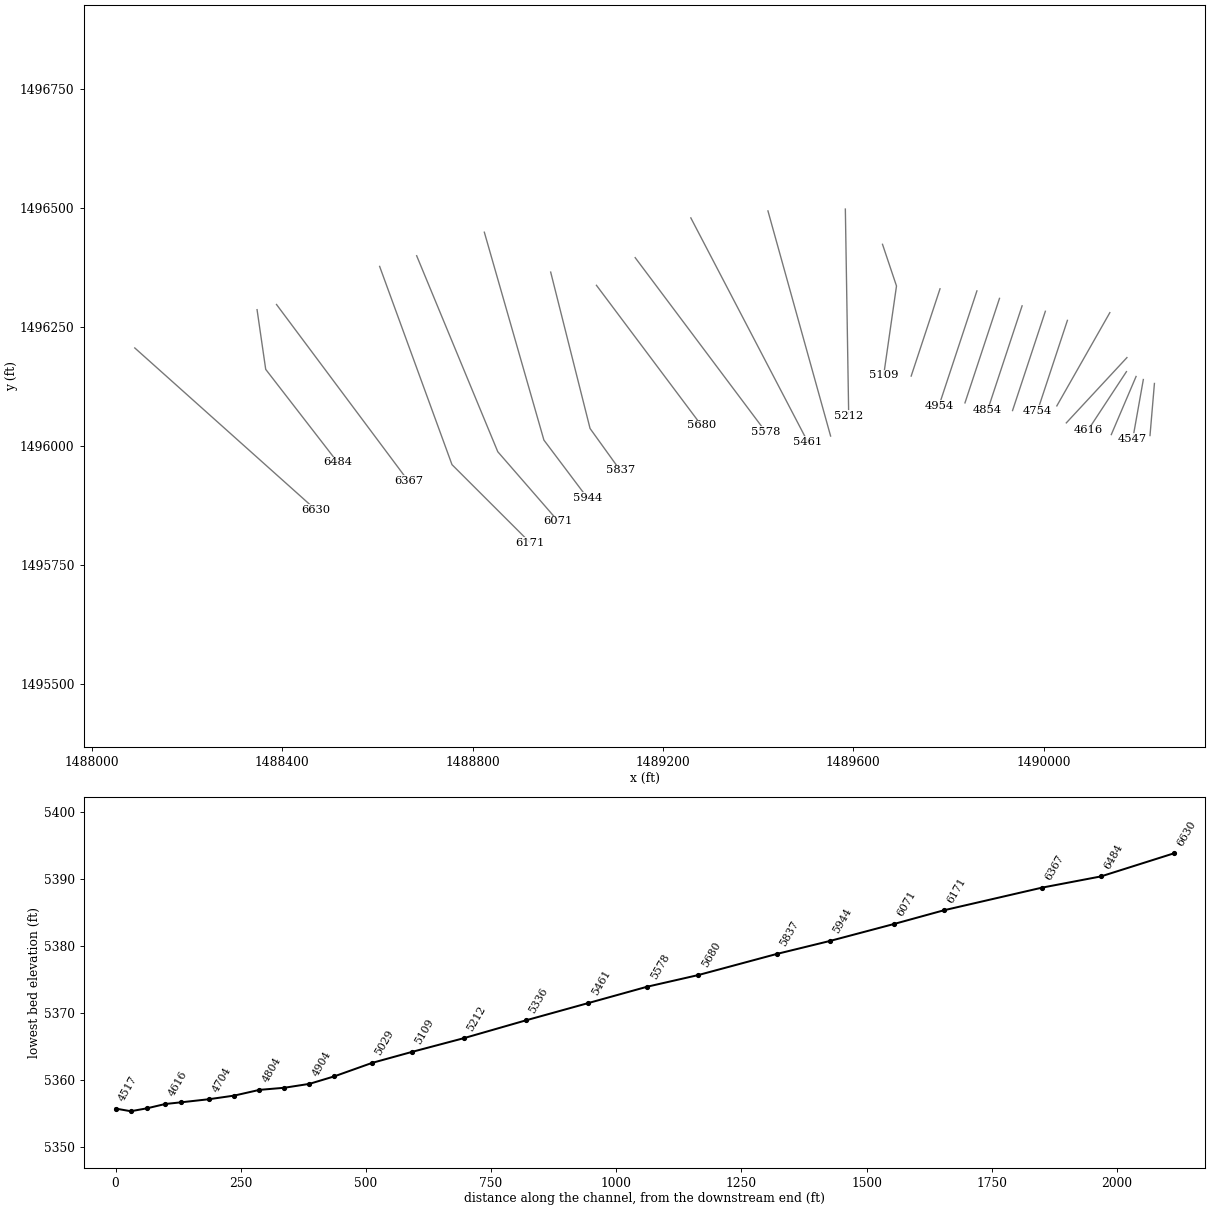
HEC-RAS study MirehavenArroyo.prj: MirehavenArroyo

--- MirehavenArroyo.g01 (geometry) --- (continued)

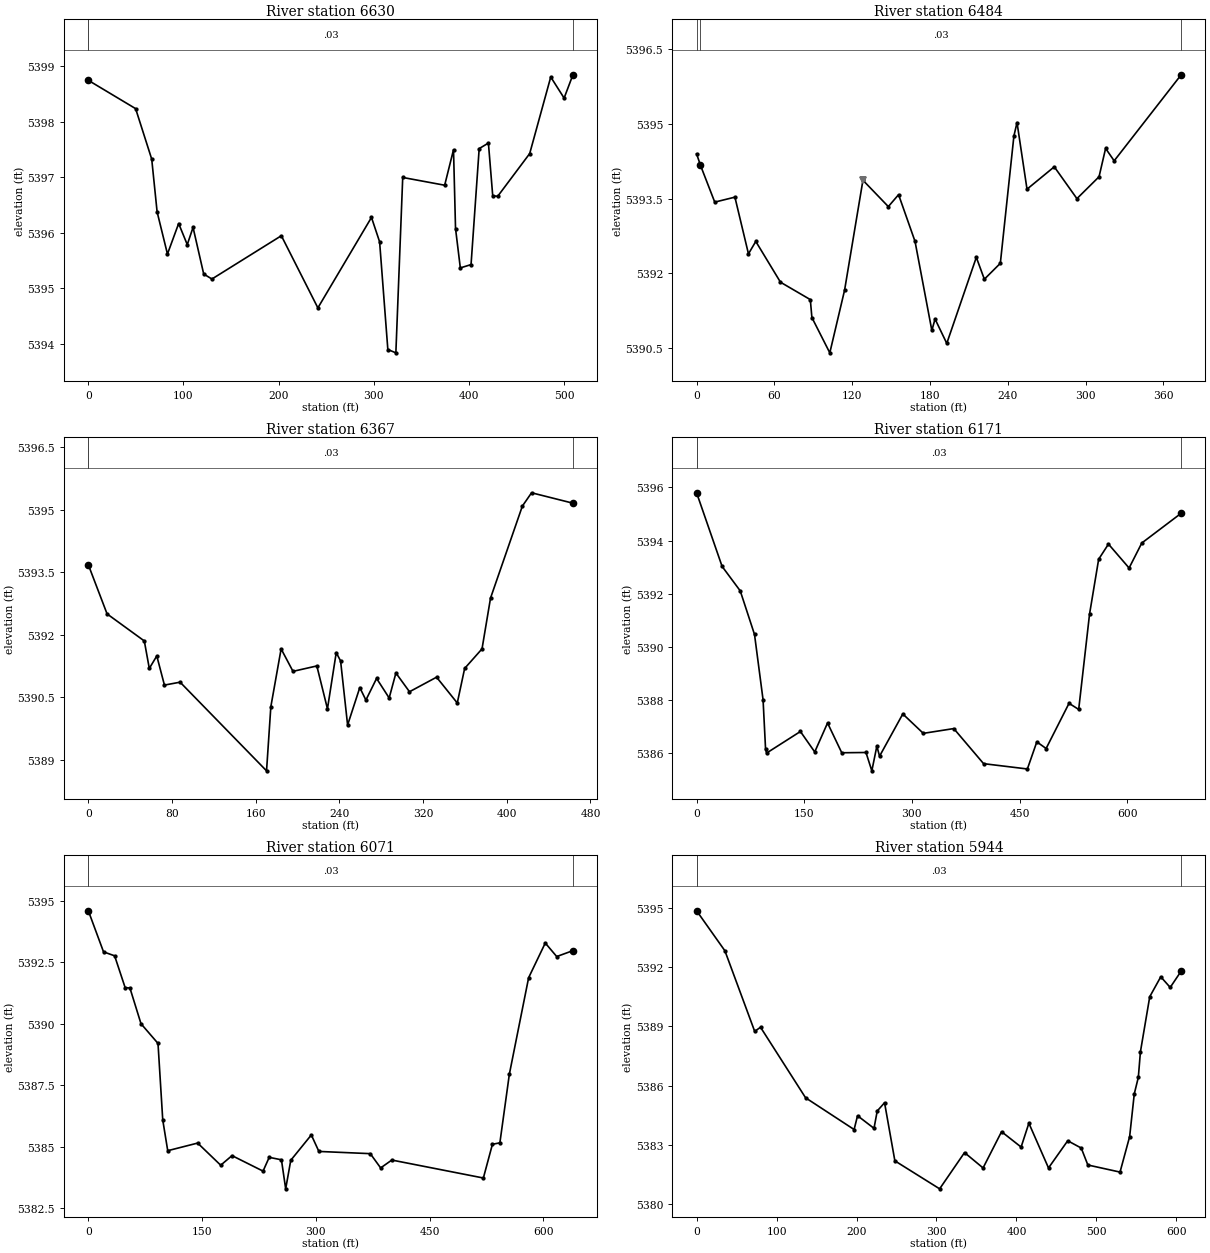
Type RM Length L Ch R = 1 ,6630    ,268.77,145.35,109.59
XS GIS Cut Line= 3
1488090.370036231496205.874986931488285.051430581496031.77521273
1488470.005879181495866.37405641
#Sta/Elev= 30
       0 5398.75   49.69 5398.24   66.62 5397.33   72.28 5396.3883.15997 5395.62
94.91998 5396.17  103.98 5395.79  110.06  5396.1  121.26 5395.26   129.9 5395.17
  202.86 5395.95  241.25 5394.65  297.59 5396.28  306.13 5395.84  314.78  5393.9
  323.21 5393.84  330.42    5397  374.51 5396.86   383.8  5397.5  385.92 5396.08
  390.96 5395.37  402.23 5395.43  410.78 5397.52  420.48 5397.62  425.01 5396.67
  430.22 5396.66  463.86 5397.43  485.99 5398.81  500.04 5398.43   509.3 5398.85
#Mann= 3 , 0 , 0
       0    .045       0       0     .03       0   509.3    .045       0
Bank Sta=0,509.3
XS Rating Curve= 0 ,0
Exp/Cntr=0.3,0.1

Type RM Length L Ch R = 1 ,6484    ,42.76,117.27,165.25
XS GIS Cut Line= 4
1488347.261574741496286.287167861488365.43190146 1496160.8872799
1488380.544446051496141.357229741488516.554779811495965.59009639
#Sta/Elev= 30
       0  5394.4 2.98999 5394.1713.98999 5393.4329.54001 5393.5339.98999 5392.39
45.63998 5392.6464.67999 5391.82   87.69 5391.4788.89999 5391.11  102.71  5390.4
  114.11 5391.66  128.26 5393.87  147.84 5393.34  155.74 5393.58  168.43 5392.64
  181.39 5390.85  183.87 5391.08   192.9 5390.59  215.69 5392.32  221.88 5391.88
   234.2  5392.2  244.67 5394.76  247.07 5395.03  254.77 5393.69   275.8 5394.14
  293.26  5393.5  310.31 5393.94  315.37 5394.51  321.97 5394.26  373.65 5395.99
#Mann= 3 , 0 , 0
       0    .045       0 2.98999     .03       0  373.65    .045       0
Levee=-1,128.26,5393.87,0,,,,
Bank Sta=2.98999,373.65
XS Rating Curve= 0 ,0
Exp/Cntr=0.3,0.1

Type RM Length L Ch R = 1 ,6367    ,230.95,196.37,296.88
XS GIS Cut Line= 4
1488388.102227211496297.177983241488486.437608271496165.45264562
1488661.189139951495931.363915161488665.980265081495926.67317833
#Sta/Elev= 30
       0 5393.6817.91998  5392.553.50998 5391.85   58.28 5391.19   65.44 5391.49
72.73999 5390.79   87.72 5390.86  170.35 5388.73  174.45 5390.27  184.28 5391.66
  195.63 5391.12  218.43 5391.25  228.57 5390.22  236.96 5391.57  241.13 5391.37
  247.83 5389.83  259.48 5390.73  265.32 5390.43  275.53 5390.95  287.56 5390.48
  294.01 5391.08  306.99 5390.63  332.87 5390.98  352.66 5390.36  359.71 5391.19
  376.32 5391.66  384.45 5392.88  414.88 5395.09  423.68 5395.41  463.21 5395.16
#Mann= 3 , 0 , 0
       0    .045       0       0     .03       0  463.21    .045       0
Bank Sta=0,463.21
XS Rating Curve= 0 ,0
Exp/Cntr=0.3,0.1

Type RM Length L Ch R = 1 ,6171    ,80.93,99.7,74.24
XS GIS Cut Line= 4
1488604.756336651496377.180328831488682.791468081496163.36495962
1488756.740960881495960.744193621488920.843041211495796.90037295
#Sta/Elev= 30
       0  5395.835.54004 5393.03   60.81 5392.1180.70001 5390.47   92.63 5388.01
96.10999 5386.1597.60004 5386.01  144.65 5386.82   164.6 5386.05  182.46 5387.14
  202.26 5386.02  236.02 5386.03  244.16 5385.34  251.17 5386.27  254.91 5385.89
  287.32 5387.48  315.88 5386.75  358.34 5386.93  399.88 5385.61  460.88 5385.41
  474.05 5386.43     487 5386.18  518.93 5387.88  532.39 5387.65  547.53 5391.24
  560.21  5393.3  573.88 5393.87  602.61 5392.97  620.32 5393.91   675.2 5395.03
#Mann= 3 , 0 , 0
       0    .045       0       0     .03       0   675.2    .045       0
Bank Sta=0,675.2
XS Rating Curve= 0 ,0
Exp/Cntr=0.3,0.1

Type RM Length L Ch R = 1 ,6071    ,150.52,127.63,78.52
XS GIS Cut Line= 4
1488682.526559851496399.589137981488782.355359281496158.38266202
1488852.916264861495987.893309551488979.727625491495842.10492195
#Sta/Elev= 30
       0 5394.5920.02997 5392.9234.64996 5392.7648.48999 5391.4754.84998 5391.45
69.41998    539091.83997  5389.298.08997 5386.09  104.66 5384.84  144.12 5385.15
  174.48 5384.25  189.41 5384.64  230.32 5384.01  238.41 5384.57  254.55 5384.47
  260.15 5383.29  266.85 5384.45  293.95 5385.48  303.92 5384.81  371.67 5384.72
  385.33 5384.14  400.07 5384.46  520.73 5383.73  532.67  5385.1   542.5 5385.16
     555 5387.95   580.4 5391.87  602.34 5393.28  617.42 5392.73  638.79 5392.97
#Mann= 3 , 0 , 0
       0    .045       0       0     .03       0  638.79    .045       0
Bank Sta=0,638.79
XS Rating Curve= 0 ,0
Exp/Cntr=0.3,0.1

Type RM Length L Ch R = 1 ,5944    ,162.61,106.6,89.91
XS GIS Cut Line= 4
1488824.689643891496449.038466661488909.766816921496152.18636396
1488949.85688106 1496012.30372081489041.082790131495891.08001685
#Sta/Elev= 30
       0 5394.8735.40002 5392.8472.66003 5388.7579.95001 5388.96  136.31 5385.38
  196.99 5383.77  201.28 5384.47  221.86 5383.83   225.9 5384.71  235.06 5385.13
  247.97 5382.18  303.94 5380.76  335.08  5382.6  358.25 5381.82  381.39 5383.66
  405.84 5382.88  415.55 5384.09   440.1 5381.82  464.13  5383.2  481.03 5382.83
  489.31 5381.97  529.55 5381.61  541.57 5383.41547.3701 5385.58  552.44 5386.42
  555.04 5387.71  566.71 5390.51   580.5 5391.52   592.3 5390.98  606.03 5391.81
#Mann= 3 , 0 , 0
       0    .045       0       0     .03       0  606.03    .045       0
Bank Sta=0,606.03
XS Rating Curve= 0 ,0
Exp/Cntr=0.3,0.1

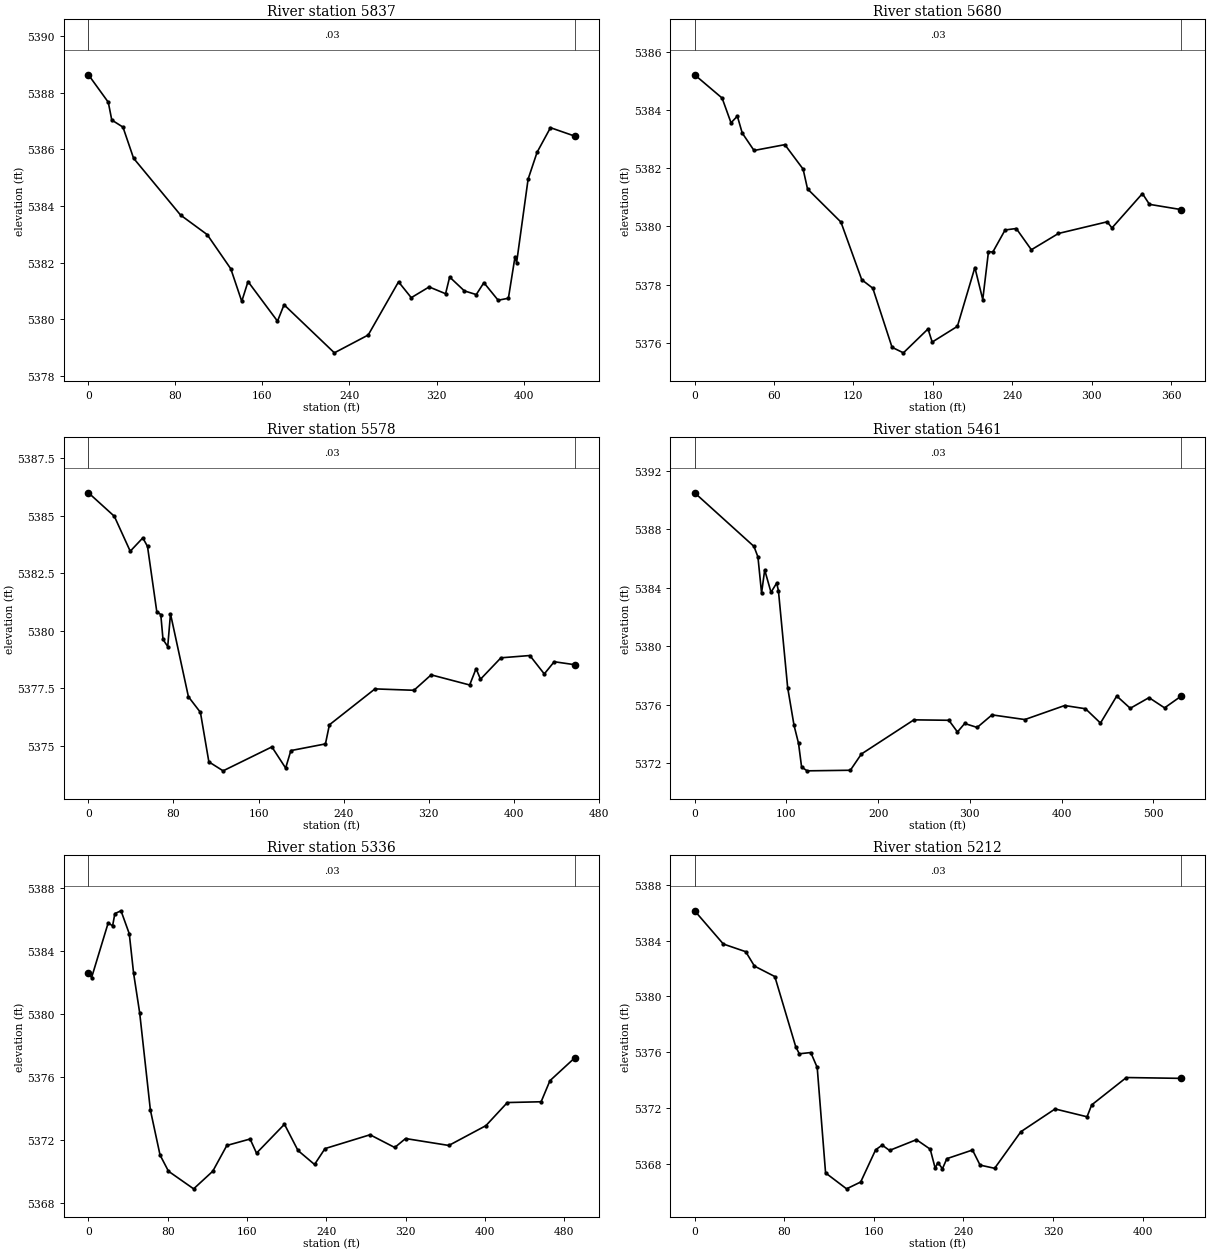
Type RM Length L Ch R = 1 ,5837    ,100.09,156.57,195.37
XS GIS Cut Line= 4
1488964.065120221496365.267695781489016.198791471496158.23020822
1489046.797497251496036.714132051489110.091713921495948.70608248
#Sta/Elev= 30
       0 5388.64   18.25 5387.67   21.47 5387.04   31.75 5386.79    41.5 5385.69
   84.72 5383.68  109.18 5382.99   130.9 5381.78  140.96 5380.63  146.72 5381.33
  173.82 5379.93  179.86 5380.51  226.11 5378.81  257.21 5379.44  285.09 5381.32
   296.8 5380.76  313.24 5381.14  328.35  5380.9  332.08 5381.49  345.61    5381
  356.56 5380.87  363.55 5381.29  376.66 5380.67   386.1 5380.74   392.2 5382.21
  393.65    5382  404.21 5384.95  412.47  5385.9  424.77 5386.77  447.21 5386.47
#Mann= 3 , 0 , 0
       0    .045       0       0     .03       0  447.21    .045       0
Bank Sta=0,447.21
XS Rating Curve= 0 ,0
Exp/Cntr=0.3,0.1

Type RM Length L Ch R = 1 ,5680    ,99.99,101.94,141.39
XS GIS Cut Line= 3
1489060.209108281496337.454489331489165.392454821496197.11320789
1489280.670566951496043.30294693
#Sta/Elev= 30
       0 5385.21   20.75 5384.4127.49002 5383.5632.27002 5383.7935.95001 5383.21
   44.87 5382.61   68.16 5382.8181.95999 5381.9785.30002 5381.29  110.56 5380.15
  126.28 5378.17  134.63 5377.88  149.18 5375.85  157.75 5375.66  176.35 5376.48
  179.51 5376.03  198.56 5376.57  211.76 5378.59  217.72 5377.49  222.05 5379.14
   225.3 5379.12  234.61 5379.88  243.03 5379.93  254.45  5379.2  274.92 5379.76
  311.73 5380.16  315.37 5379.95  338.37 5381.13  343.68 5380.76   367.6 5380.58
#Mann= 3 , 0 , 0
       0    .045       0       0     .03       0   367.6    .045       0
Bank Sta=0,367.6
XS Rating Curve= 0 ,0
Exp/Cntr=0.3,0.1

Type RM Length L Ch R = 1 ,5578    ,143.68,117.46,90.21
XS GIS Cut Line= 3
1489141.582139831496395.567085911489246.059338571496256.16798485
1489416.011730221496029.40835784
#Sta/Elev= 30
       0    538624.35999 5384.9839.32999 5383.4651.15997 5384.0455.56998 5383.67
64.28998 5380.84   68.06 5380.7170.14999 5379.6374.59998 5379.3277.19998 5380.74
94.04999 5377.14  105.35 5376.46  113.29 5374.31   126.7 5373.92  172.58 5374.96
  185.52 5374.04  190.43  5374.8  222.96 5375.09  226.68 5375.92  269.56 5377.48
  306.22 5377.42  322.38 5378.09  358.62 5377.65  364.64 5378.36   368.8  5377.9
  388.02 5378.83  415.23 5378.93   428.8 5378.13  438.15 5378.66  457.58 5378.53
#Mann= 3 , 0 , 0
       0    .045       0       0     .03       0  457.58    .045       0
Bank Sta=0,457.58
XS Rating Curve= 0 ,0
Exp/Cntr=0.3,0.1

Type RM Length L Ch R = 1 ,5461    ,162.65,124.92,57.58
XS GIS Cut Line= 3
1489258.506683851496479.068815271489344.417208941496314.47646404
1489503.875218951496008.97758877
#Sta/Elev= 30
       0 5390.5164.65002 5386.8468.99002 5386.1272.95004 5383.6476.35004 5385.23
83.23004  5383.789.43002 5384.3391.33002 5383.81  101.39 5377.18  108.35 5374.59
  113.25 5373.36  116.58 5371.74  122.62 5371.48  169.74 5371.52  181.74 5372.63
  239.01 5374.97  277.14 5374.94  286.48 5374.14  294.38 5374.72  307.97 5374.45
  324.17 5375.31  359.95 5374.99  403.37 5375.95  426.03 5375.73   442.4 5374.75
  460.13  5376.6  474.87 5375.76   495.3 5376.49  512.28 5375.79  530.28 5376.59
#Mann= 3 , 0 , 0
       0    .045       0       0     .03       0  530.28    .045       0
Bank Sta=0,530.28
XS Rating Curve= 0 ,0
Exp/Cntr=0.3,0.1

Type RM Length L Ch R = 1 ,5336    ,162.65,124.29,56.97
XS GIS Cut Line= 3
1489420.490024081496493.788438421489463.650401731496338.69314699
1489552.105161171496020.83409574
#Sta/Elev= 30
       0 5382.613.199982 5382.3319.94998 5385.8124.38998 5385.62   26.69  5386.4
   32.87 5386.58   41.22 5385.1245.57999 5382.61   51.72 5380.0962.50998 5373.91
   72.28 5371.0480.78998 5370.01  106.19 5368.89  125.48 5370.01  139.69 5371.65
  163.17 5372.06  169.64 5371.16  197.84    5373  211.49 5371.33   228.2 5370.44
  238.75 5371.45  284.22 5372.33  309.13 5371.52  320.06 5372.09  363.73 5371.65
  401.15 5372.91  422.79 5374.38  456.88 5374.43  465.77 5375.77  490.93 5377.23
#Mann= 3 , 0 , 0
       0    .045       0       0     .03       0  490.93    .045       0
Bank Sta=0,490.93
XS Rating Curve= 0 ,0
Exp/Cntr=0.3,0.1

Type RM Length L Ch R = 1 ,5212    ,107.59,103.01,119.05
XS GIS Cut Line= 3
1489583.096693821496497.625477761489586.030543111496316.95758305
1489590.150733631496063.23420696
#Sta/Elev= 30
       0 5386.1325.62003 5383.7545.62003  5383.253.39001 5382.1771.61002 5381.42
90.26001  5376.4   93.47 5375.89  103.72 5375.98  109.46 5374.91  116.93 5367.36
  135.69 5366.22  148.29 5366.71  161.67 5369.02  167.53 5369.35  174.03 5368.97
  198.08 5369.74  210.38 5369.06  214.81  5367.7  217.22  5368.1  221.32 5367.66
  225.23 5368.38  248.15    5369  254.91 5367.92  267.92 5367.69  291.35 5370.31
  321.91 5371.94  350.45 5371.38   354.6 5372.23  385.56 5374.19  434.45 5374.13
#Mann= 3 , 0 , 0
       0    .045       0       0     .03       0  434.45    .045       0
Bank Sta=0,434.45
XS Rating Curve= 0 ,0
Exp/Cntr=0.3,0.1

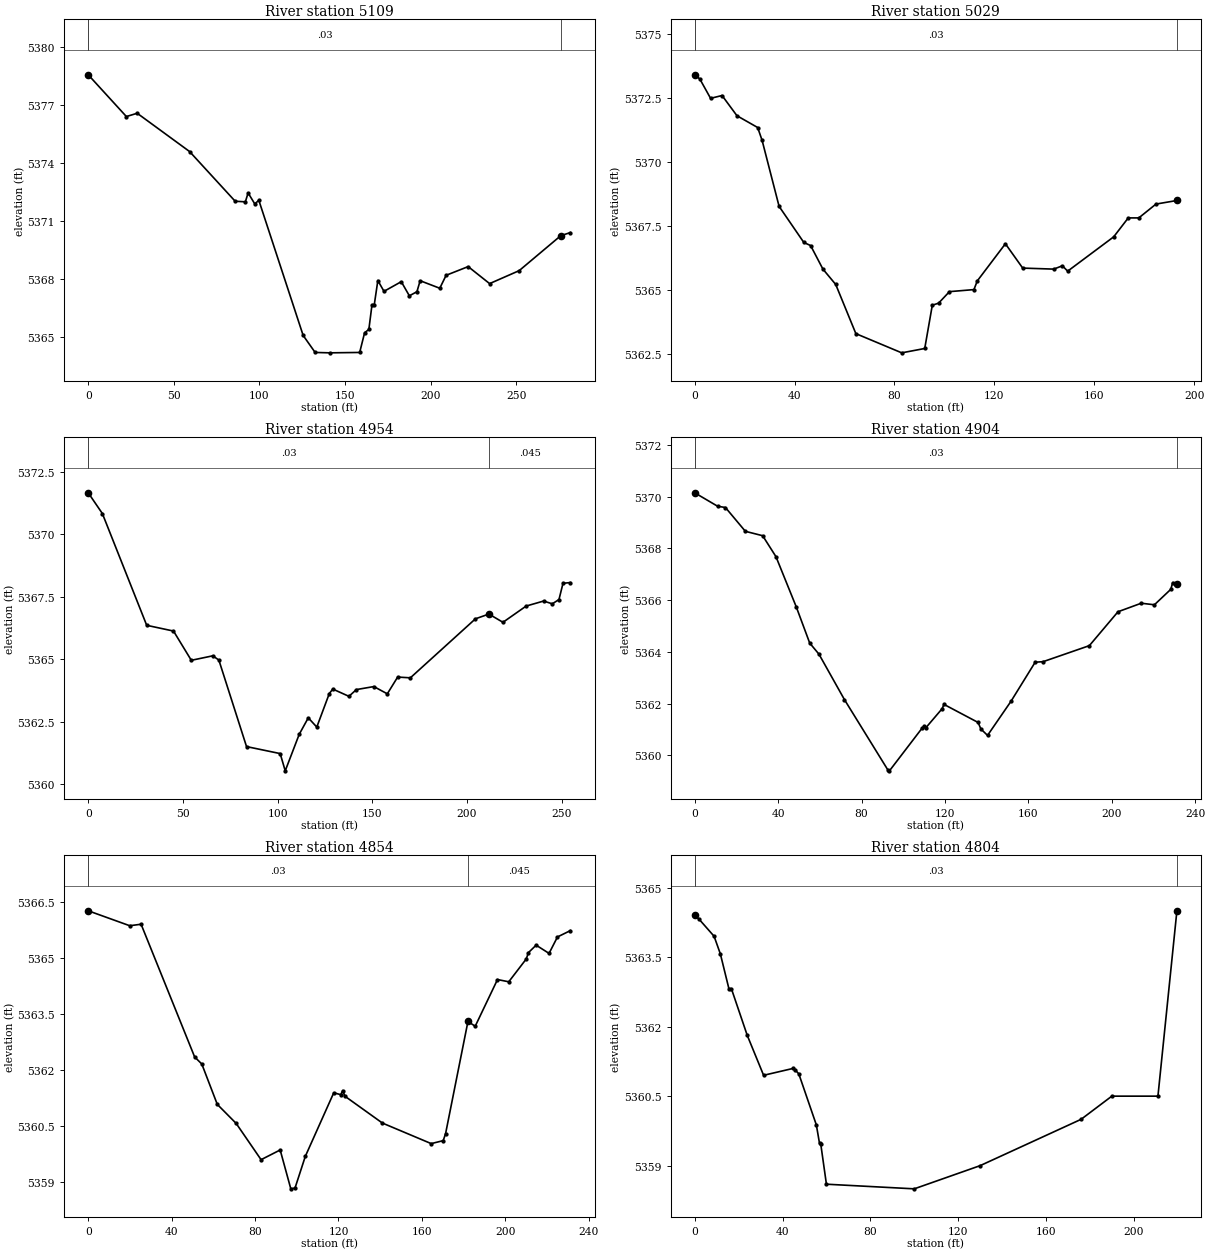
Type RM Length L Ch R = 1 ,5109    ,152.73,79.99,57.46
XS GIS Cut Line= 4
1489661.152679191496423.582269461489690.541239631496336.06103281
1489683.234479561496285.217144321489663.604837141496148.62481883
#Sta/Elev= 30
       0 5378.5622.29001  5376.4   28.61 5376.57   59.22 5374.5985.85001 5372.02
    91.8 5371.99   93.41 5372.45   97.31 5371.88   99.66 5372.07  125.56 5365.08
  132.56  5364.2  141.09 5364.18  158.58  5364.2  161.46 5365.22  163.94 5365.39
  165.78 5366.67  167.11 5366.67  169.19 5367.92  172.78 5367.36  182.88 5367.86
  187.59 5367.13  192.02 5367.34   193.9 5367.91  205.37 5367.52  209.07 5368.19
  221.95 5368.64  234.48 5367.76  251.74 5368.43  276.06 5370.24  281.69  5370.4
#Mann= 3 , 0 , 0
       0    .045       0       0     .03       0  276.06    .045       0
Bank Sta=0,276.06
XS Rating Curve= 0 ,0
Exp/Cntr=0.3,0.1

Type RM Length L Ch R = 1 ,5029    ,77.62,74.98,79.69
XS GIS Cut Line= 3
 1489781.97347081496330.159836541489756.833643191496254.08747665
1489721.383598421496146.81671066
#Sta/Elev= 30
       0 5373.392.029999 5373.236.360001 5372.4710.96001 5372.5816.93001 5371.79
   25.22 5371.3326.99001 5370.83    33.8 5368.2543.71001 5366.8446.42001 5366.72
51.35001  5365.856.48001  5365.264.54001 5363.28   82.91 5362.53   92.12  5362.7
95.15001 5364.39   97.66 5364.47  102.01 5364.92  111.82    5365  113.17 5365.34
  124.42 5366.79  131.35 5365.84  143.78  5365.8  147.24 5365.93  149.36 5365.72
  167.78 5367.06  173.62  5367.8  177.84  5367.8  184.72 5368.34   193.1 5368.48
#Mann= 3 , 0 , 0
       0    .045       0       0     .03       0   193.1    .045       0
Bank Sta=0,193.1
XS Rating Curve= 0 ,0
Exp/Cntr=0.3,0.1

Type RM Length L Ch R = 1 ,4954    ,49.98,49.98,54.32
XS GIS Cut Line= 3
1489859.470157261496325.722540061489828.236532141496231.21053275
1489779.560130921496083.91721119
#Sta/Elev= 30
       0 5371.657.470001 5370.82   30.89 5366.3545.03999 5366.12   54.45 5364.95
    65.8 5365.13      69 5364.96   83.61  5361.5  101.38 5361.22  104.05 5360.53
  111.43 5361.99  116.22 5362.65  120.72 5362.28  127.32 5363.62  129.16  5363.8
  137.69 5363.51  141.65 5363.78  150.85  5363.9  157.96 5363.61  163.42 5364.28
  170.14 5364.25  204.51 5366.61  211.62  5366.8  219.04 5366.47  231.29 5367.12
  240.51 5367.32  245.09 5367.21  248.62 5367.38  250.75 5368.03  254.67 5368.06
#Mann= 3 , 0 , 0
       0    .045       0       0     .03       0  211.62    .045       0
Bank Sta=0,211.62
XS Rating Curve= 0 ,0
Exp/Cntr=0.3,0.1

Type RM Length L Ch R = 1 ,4904    ,49.98,49.99,51.54
XS GIS Cut Line= 3
1489906.929123981496310.03865378 1489875.83845811496215.95923682
1489834.376343951496090.49613028
#Sta/Elev= 30
       0 5370.15   10.98 5369.63   14.75 5369.58    24.3 5368.66   32.59 5368.49
   38.97 5367.68    48.7 5365.7455.14999 5364.34   59.59 5363.91   71.83 5362.15
   92.66 5359.43   93.38  5359.4  109.13 5361.06  110.07 5361.13  110.89 5361.07
  118.73 5361.81   119.5 5361.97   135.9 5361.27  137.21 5361.02  140.42 5360.77
  151.68 5362.09  163.26  5363.6  167.04 5363.62  189.24 5364.24  202.97 5365.55
  214.12 5365.88  220.44 5365.82  228.32 5366.42  229.18 5366.68  231.22 5366.61
#Mann= 3 , 0 , 0
       0    .045       0       0     .03       0  231.22    .045       0
Bank Sta=0,231.22
XS Rating Curve= 0 ,0
Exp/Cntr=0.3,0.1

Type RM Length L Ch R = 1 ,4854    ,50.18,49.98,50.74
XS GIS Cut Line= 3
1489954.388090711496294.354767491489923.440384071496200.70794089
1489881.837954161496074.82024311
#Sta/Elev= 30
       0 5366.2619.90001 5365.8625.35001  5365.9   51.02 5362.3554.46001 5362.16
   61.89 5361.0870.95001 5360.57   82.88  5359.692.04001 5359.86   97.14 5358.82
99.15001 5358.84   104.1 5359.69  117.73 5361.39  121.08 5361.34  122.03 5361.45
  123.04  5361.3  141.06 5360.58  164.46 5360.03  170.22 5360.11  171.36  5360.3
  182.08  5363.3  185.55 5363.17  196.24 5364.42  201.64 5364.36  210.02 5364.97
  211.07 5365.14  214.76 5365.34  220.96 5365.12     225 5365.56  231.21 5365.73
#Mann= 3 , 0 , 0
       0    .045       0       0     .03       0  182.08    .045       0
Bank Sta=0,182.08
XS Rating Curve= 0 ,0
Exp/Cntr=0.3,0.1

Type RM Length L Ch R = 1 ,4804    ,50.11,50.01,50.01
XS GIS Cut Line= 3
1490003.24988179 1496282.91578541489971.003410691496185.33893671
 1489934.33196781496074.37225688
#Sta/Elev= 21
       0  5364.41.960007 5364.328.839996 5363.95   11.69 5363.57   15.63 5362.81
16.71001 5362.82   23.95 5361.81   31.39 5360.95   44.97  5361.145.89999 5361.06
47.42999 5360.98   55.41 5359.88   56.86 5359.48   57.44 5359.46      60  5358.6
     100  5358.5     130    5359     176    5360     190  5360.5     211  5360.5
  219.64  5364.5
#Mann= 3 , 0 , 0
       0    .045       0       0     .03       0  219.64    .045       0
Bank Sta=0,219.64
XS Rating Curve= 0 ,0
Exp/Cntr=0.3,0.1

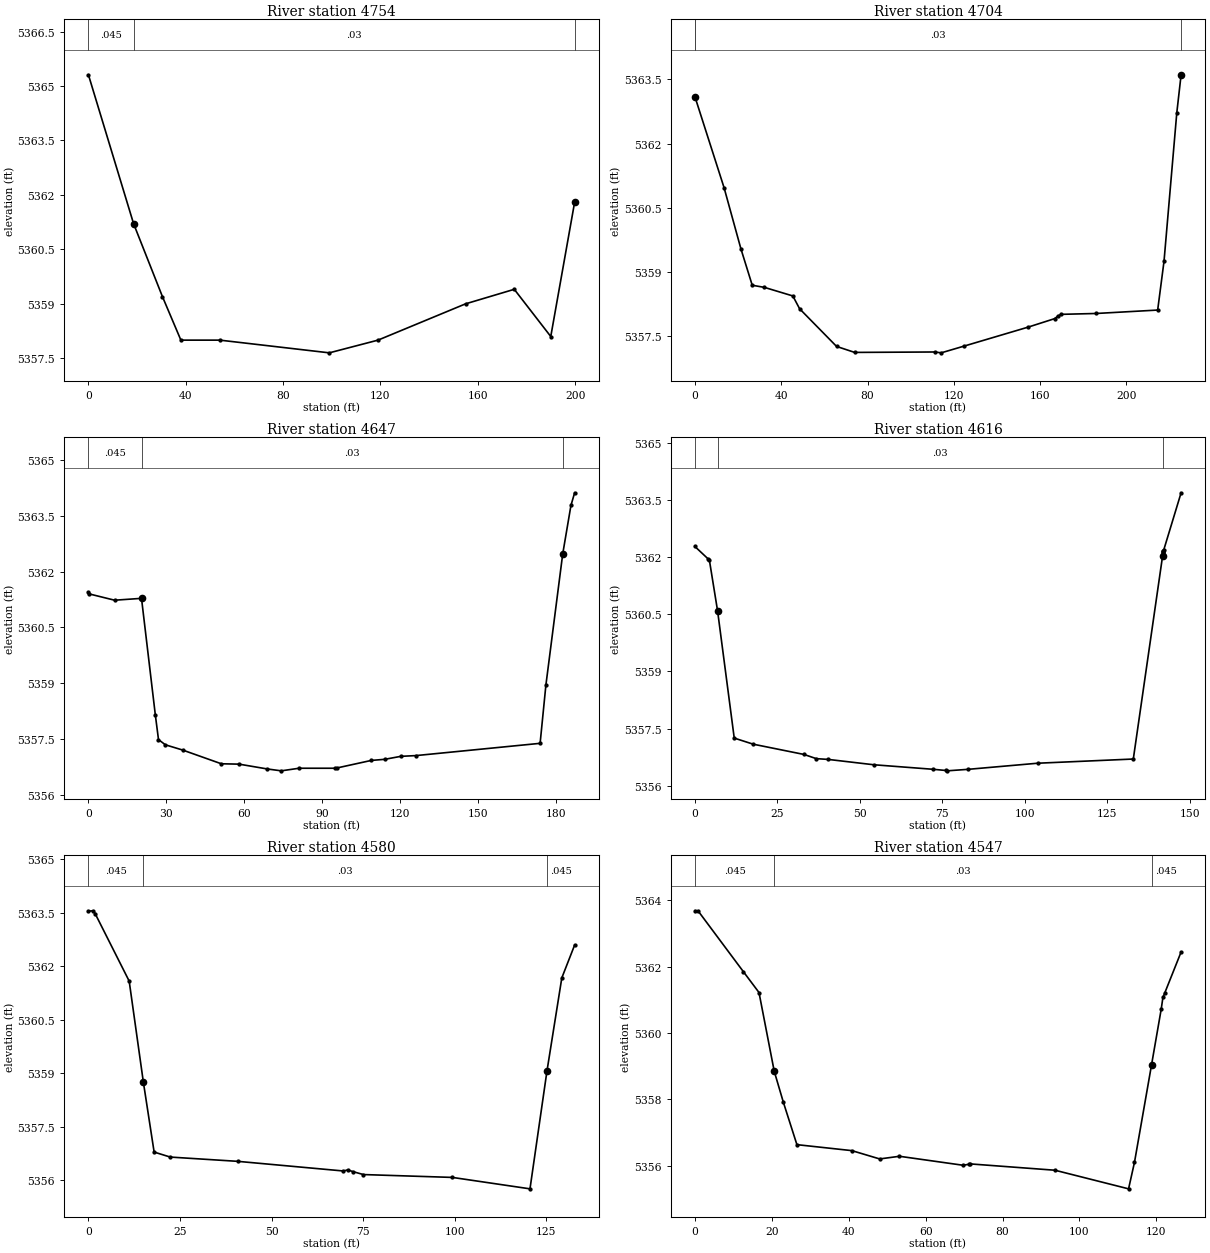
Type RM Length L Ch R = 1 ,4754    ,71.46,50.25,32.14
XS GIS Cut Line= 3
1490049.578427871496263.811280371490018.025683941496168.33362917
1489986.881210111496074.09139097
#Sta/Elev= 11
       0 5365.31   18.55 5361.21   30.41  5359.2      38    5358      54    5358
      99 5357.65     119    5358     155    5359     175  5359.4     190  5358.1
  199.81  5361.8
#Mann= 3 , 0 , 0
       0    .045       0   18.55     .03       0  199.81    .045       0
Bank Sta=18.55,199.81
XS Rating Curve= 0 ,0
Exp/Cntr=0.3,0.1

Type RM Length L Ch R = 1 ,4704    ,78.51,56.37,37.82
XS GIS Cut Line= 3
 1490138.70462771496280.025729291490063.930686531496148.50438968
1490027.339158991496084.14284013
#Sta/Elev= 21
       0  5363.1   13.53 5360.97   21.34 5359.54   26.58 5358.69   32.23 5358.64
   45.39 5358.4448.54001 5358.14   65.66 5357.26   74.05 5357.12  111.15 5357.13
  114.15 5357.11  124.92 5357.27  154.36 5357.71  166.77 5357.91  168.23 5357.97
  169.73 5358.01   185.9 5358.03  214.47 5358.11  217.41 5359.25  223.33 5362.72
  225.33 5363.61
#Mann= 3 , 0 , 0
       0    .045       0       0     .03       0  225.33    .045       0
Bank Sta=0,225.33
XS Rating Curve= 0 ,0
Exp/Cntr=0.3,0.1

Type RM Length L Ch R = 1 ,4647    ,46.6,31.46,21.56
XS GIS Cut Line= 3
1490174.624374161496185.634626341490109.412493611496115.39119514
 1490047.27355771496048.45780766
#Sta/Elev= 24
       0 5361.44 .269989  5361.410.07999 5361.2320.43999 5361.28   25.75 5358.15
   26.98 5357.48   29.64 5357.34   36.25  5357.2   51.17 5356.8358.00999 5356.82
   68.91 5356.6974.23999 5356.6481.10999 5356.7194.95999 5356.7195.84999 5356.72
  108.89 5356.92  114.09 5356.95  120.26 5357.03  126.06 5357.05  173.89 5357.38
  176.12 5358.95  182.58 5362.47  185.76 5363.78  187.18 5364.12
#Mann= 3 , 0 , 0
       0    .045       020.43999     .03       0  182.58    .045       0
Bank Sta=20.43999,182.58
XS Rating Curve= 0 ,0
Exp/Cntr=0.3,0.1

Type RM Length L Ch R = 1 ,4616    ,26.69,35.53,47.5
XS GIS Cut Line= 3
1490173.576956041496156.115680451490133.86149639 1496095.6832844
1490092.622785431496032.93305727
#Sta/Elev= 23
       0 5362.283.939987 5361.964.399994 5361.92 6.87999 5360.5911.92999 5357.25
   17.67 5357.09   33.09 5356.82   36.81 5356.71   40.41 5356.69    54.2 5356.55
   72.31 5356.43   75.98  5356.476.42999 5356.3982.88999 5356.43  103.92 5356.59
  132.91  5356.7  141.77 5362.02  141.88  5362.1  141.93 5362.13  141.96 5362.15
     142 5362.16  142.14 5362.19   147.4 5363.69
#Mann= 3 , 0 , 0
       0    .045       0 6.87999     .03       0  141.77    .045       0
Bank Sta=6.87999,141.77
XS Rating Curve= 0 ,0
Exp/Cntr=0.3,0.1

Type RM Length L Ch R = 1 ,4580    ,22.31,33.1,43.93
XS GIS Cut Line= 3
1490193.836248651496145.975747161490165.477362691496079.46487007
1490141.771868871496023.86772185
#Sta/Elev= 17
       0 5363.54 1.37001 5363.551.889999 5363.46   11.13 5361.5815.00001 5358.75
   17.94 5356.79   22.34 5356.65    40.8 5356.53   69.61 5356.26    70.8 5356.29
    72.3 5356.24   75.08 5356.16   99.36 5356.08  120.55 5355.76  125.17 5359.05
  129.24 5361.67  132.74 5362.59
#Mann= 3 , 0 , 0
       0    .045       015.00001     .03       0  125.17    .045       0
Bank Sta=15.00001,125.17
XS Rating Curve= 0 ,0
Exp/Cntr=0.3,0.1

Type RM Length L Ch R = 1 ,4547    ,35.98,30.53,37.96
XS GIS Cut Line= 3
1490209.073106851496139.552822731490196.582196441496069.33590546
1490186.932588551496015.09120299
#Sta/Elev= 21
       0 5363.68.8099976 5363.68   12.59 5361.85   16.67 5361.22   20.63 5358.85
   23.02 5357.91   26.53 5356.64   40.82 5356.46   48.05 5356.2153.18999 5356.29
   69.72 5356.02   71.32 5356.05   71.66 5356.06   93.63 5355.87  112.76 5355.31
   114.3 5356.11  118.73 5359.04  121.25 5360.72  121.69 5361.07  122.15  5361.2
  126.42 5362.44
#Mann= 3 , 0 , 0
       0    .045       0   20.63     .03       0  118.73    .045       0
Bank Sta=20.63,118.73
XS Rating Curve= 0 ,0
Exp/Cntr=0.3,0.1

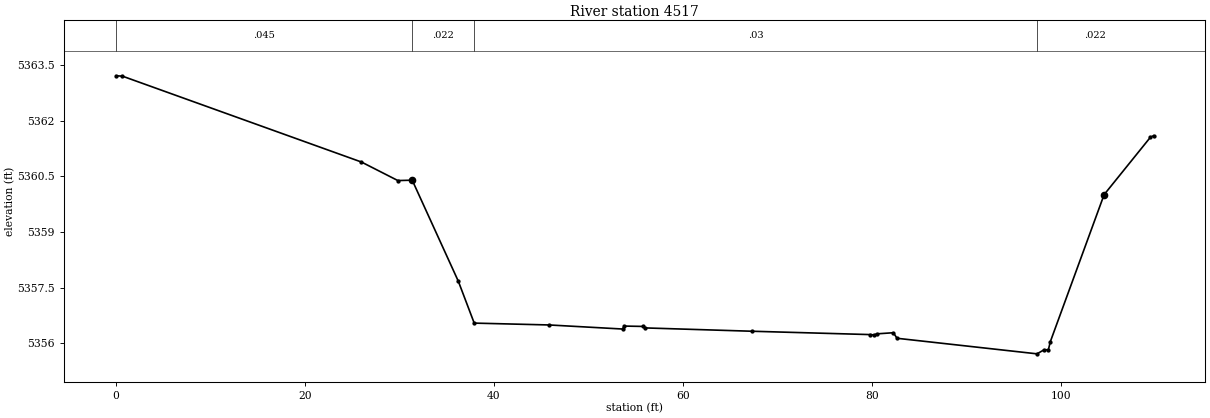
Type RM Length L Ch R = 1 ,4517    ,6,6.02,6
XS GIS Cut Line= 3
1490232.392223061496131.290798281490226.680018061496064.18839776
1490223.079103371496021.88774172
#Sta/Elev= 25
       0 5363.22.6800003 5363.21   25.98 5360.89   29.83 5360.3931.35001  5360.4
   36.23 5357.67   37.91 5356.54   45.84 5356.49   53.62 5356.38   53.79 5356.46
   55.82 5356.45   56.01 5356.4167.35001 5356.32    79.8 5356.23   80.26 5356.22
   80.52 5356.25   82.26 5356.28   82.66 5356.13   97.47 5355.71   98.22 5355.82
98.67001 5355.82   98.88 5356.04  104.57 5360.01  109.47 5361.56   109.8  5361.6
#Mann= 4 ,-1 , 0
       0    .045       031.35001    .022       0   37.91     .03       0
   97.47    .022       0
Bank Sta=31.35001,104.57
XS Rating Curve= 0 ,0
Exp/Cntr=0.3,0.1